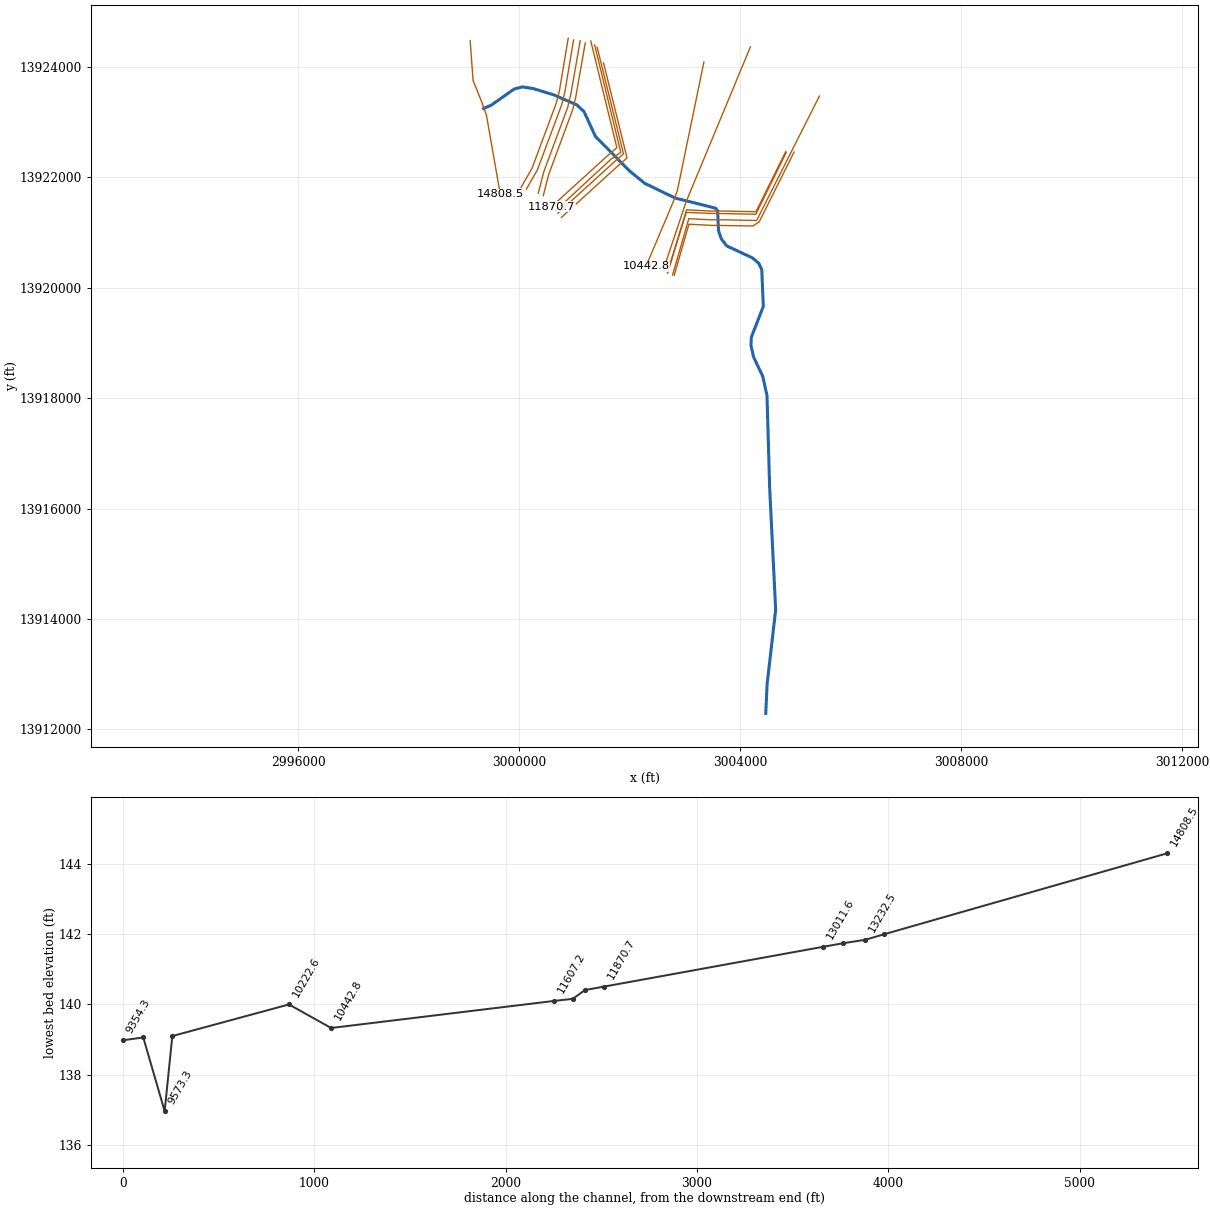
--- K159-00-00.prj (project) ---

Proj Title=K159-00-00
Current Plan=p02
Default Exp/Contr=.3,.1
English Units
Geom File=g01
Flow File=f01
Flow File=f02
Plan File=p01
Plan File=p02
Y Axis Title=Elevation
X Axis Title(PF)=Main Channel Distance
X Axis Title(XS)=Station
BEGIN DESCRIPTION:
Cypress Creek Watershed
Cypress Creek Channel A
HCFCD Unit K159-00-00
Flood Hazard Model
10, 2, 1, 0.2%
Filename K159-00-00
Prepared by:  Halff Associates Inc  DATE:  03-26-04
Reviewed by:  _________  DATE:  __________________
STATUS (Final)
END DESCRIPTION:
DSS Export Rating Curves= 0
DSS Export Rating Curve Sorted= 0
DSS Export Volume Flow Curves= 0
DXF OffsetX= 0
DXF OffsetY= 0
DXF ScaleX= 1
DXF ScaleY= 10

--- K159-00-00.p02 (plan) ---

Plan Title=Effective FW 2012
Version=Version 3.0.1  May 2012
Short Identifier=Eff+LOMR FW
Geom File=g01
Flow File=f02
Subcritical Flow
K Sum by GR= 0
Std Step Tol= 0.01
Critical Tol= 0.01
Num of Std Step Trials= 20
Max Error Tol= 0.3
Flow Tol Ratio= 0.001
Split Flow NTrial= 30
Split Flow Tol= 0.02
Split Flow Ratio= 0.02
Log Output Level= 0
Friction Slope Method= 1
Unsteady Friction Slope Method= 2
Parabolic Critical Depth
Global Vel Dist= 0 , 0 , 0
Global Log Level= 0
CheckData=True
Encroach Param=-1 ,0,0, 2
Encroach River=K159-00-00
Encroach Reach=K159-00-00_0004
Encroach Node=14808.5
       1 4935.21  5061.7
Encroach Node=13332.5
       1 4926.96 5069.19
Encroach Node=13232.5
       1  4926.4  5069.7
Encroach Node=13173.5
       1  4926.4  5069.7
Encroach Node=13114.5
       1  4926.4  5069.7
Encroach Node=13011.6
       1 4926.26 5069.39
Encroach Node=11870.7
       1 4924.74 5065.91
Encroach Node=11768.7
       1  4924.6  5065.6
Encroach Node=11737.2
       1  4924.6  5065.6
Encroach Node=11705.7
       1  4924.6  5065.6
Encroach Node=11607.2
       1  4923.9 5064.57
Encroach Node=10442.8
       1  4913.2  5052.4
Encroach Node=10222.6
       1  4917.1  5058.2
Encroach Node=9613.3
       1 4926.92 5071.13
Encroach Node=9573.3
       1 4926.92 5071.13
Encroach Node=9553.3
       1  4928.5  5073.2
Encroach Node=9518.3
       1  4928.5  5073.2
Encroach Node=9515.6
       1  4928.5  5073.2
Encroach Node=9488.6
       1  4928.5  5073.2
Encroach Node=9461.6
       1  4928.5  5073.2
Encroach Node=9354.3
       1    4929    5063
Encroach Node=8742
       1  4932.4  5072.4
Encroach Node=7495.6
       1 4929.51  5085.9
Encroach Node=7405.3
       1  4929.3  5079.9
Encroach Node=7372.6
       1  4929.3  5079.9
Encroach Node=7339.9
       1  4929.3  5079.9
Encroach Node=7242.7
       1  4929.3  5079.9
Encroach Node=7210.75
       1  4929.3  5079.9
Encroach Node=7178.8
       1  4929.3  5079.9
Encroach Node=7127
       1  4935.6  5077.1
Encroach Node=7108
       1  4935.6  5077.1
Encroach Node=7089
       1  4935.6  5077.1
Encroach Node=6895.9
       1 4924.76 5077.06
Encroach Node=6884.4
       1 4924.76 5077.06
Encroach Node=6872.9
       1 4924.76 5077.06
Encroach Node=6771.4
       1 4925.98 5073.75
Encroach Node=5773
       1    4938  5087.9
Encroach Node=4360.4
       1    4933  5081.1
Encroach Node=3207.9
       1  4926.3  5078.6
Encroach Node=2351.
       1 4927.73  5087.3
Encroach Node=2252.2
       1  4927.9  5085.6
Encroach Node=2241.7
       1  4927.9  5085.6
Encroach Node=2231.2
       1  4930.5  5080.5
Encroach Node=2133.2
       1 4921.36  5117.6
Encroach Node=2030.4
       1 4911.56  5235.6
Encroach Node=1922.6
       1  4958.6  5296.1
Encroach Node=1894.6
       1  4958.6  5296.1
Encroach Node=1866.6
       1  4958.6  5296.1
Encroach Node=1766
       14935.725  5371.5
Encroach Node=787
       1 4936.45  5331.9
Encroach Node=736.2
       1    4940  5357.8
Encroach Node=697.8
       1    4940  5357.8
Encroach Node=659.4
       1    4940  5357.8
Encroach Node=552.7
       1  4896.3  5078.6
Encroach Node=542.2
       1  4896.3  5078.6
Encroach Node=531.7
       1  4920.7  5091.7
Encroach Node=427.6
       1  4920.7  5095.5
BEGIN DESCRIPTION:
FEMA Effective Floodway 2007 + LOMR 12-06-0478P
END DESCRIPTION:
Computation Interval=1HOUR
Output Interval=1HOUR
Run HTab= 0
Run UNet= 0
Run PostProcess= 0
UNET Theta= 1
UNET ZTol= 0.02
UNET ZSATol= 0.1
UNET MxIter= 20
UNET MaxInSteps= 20
UNET DtIC= 0
UNET DtMin= 0
UNET MaxCRTS= 20
UNET WFStab= 2
UNET SFStab= 1
UNET WFX= 1
UNET SFX= 1
UNET Convert EG Bridges=-1
UNET Use Existing IB Tables=-1
Instantaneous Interval=1HOUR
Write IC File= 0
Write Velocity= 0
Write Detailed= 0

--- K159-00-00.p01 (plan) ---

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Plan Title=Effective MP 2012
Short Identifier=Eff+LOMR MP
Geom File=g01
Flow File=f01
Encroach Param=-1 ,0,0, 0
FEMA Effective Multi-Profile 2007 + LOMR 12-06-0478P
DSS File=dss

--- K159-00-00.f02 (steady flow) ---

Flow Title=Effective FW 2012
Version=Version 3.0.1  Mar 2001
Number of Profiles= 2
Profile Names=1PCT_100yr, 1PCTFloodway_100yrFW
River Rch & RM=K159-00-00,K159-00-00_0004,14808.5
    2300    2300
River Rch & RM=K159-00-00,K159-00-00_0004,11768.7
    2700    2700
River Rch & RM=K159-00-00,K159-00-00_0004,10442.8
    2846    2846
River Rch & RM=K159-00-00,K159-00-00_0004,6895.9
    2970    2970
River Rch & RM=K159-00-00,K159-00-00_0004,5773
    3110    3110
River Rch & RM=K159-00-00,K159-00-00_0004,4360.4
    3240    3240
River Rch & RM=K159-00-00,K159-00-00_0004,3207.9
    3380    3380
River Rch & RM=K159-00-00,K159-00-00_0004,736.2
    3535    3535
Boundary for River Rch & Prof#=K159-00-00,K159-00-00_0004, 1
Up Type= 0
Dn Type= 3
Dn Slope=7.34253E-04
Boundary for River Rch & Prof#=K159-00-00,K159-00-00_0004, 2
Up Type= 0
Dn Type= 3
Dn Slope=7.34253E-04
DSS Import GetInterval= 0
DSS Import GetPeak= 0
DSS Import FillOption= 0

--- K159-00-00.f01 (steady flow) ---

Flow Title=Effective MP 2012
Version=Version 3.0.1  Mar 2001
Number of Profiles= 4
Profile Names=10PCT_10yr, 2PCT_50yr, 1PCT_100yr, 0.2PCT_500yr
River Rch & RM=K159-00-00,K159-00-00_0004,14808.5
    1300    1900    2300    3400
River Rch & RM=K159-00-00,K159-00-00_0004,11768.7
    1500    2300    2700    4000
River Rch & RM=K159-00-00,K159-00-00_0004,10442.8
    1540    2408    2846    4123
River Rch & RM=K159-00-00,K159-00-00_0004,6895.9
    1580    2500    2970    4330
River Rch & RM=K159-00-00,K159-00-00_0004,5773.0
    1630    2610    3110    4560
River Rch & RM=K159-00-00,K159-00-00_0004,4360.4
    1670    2700    3240    4760
River Rch & RM=K159-00-00,K159-00-00_0004,3207.9
    1720    2810    3380    5010
River Rch & RM=K159-00-00,K159-00-00_0004,736.2
    1772    2917    3535    5265
Boundary for River Rch & Prof#=K159-00-00,K159-00-00_0004, 1
Up Type= 0
Dn Type= 3
Dn Slope=7.34253E-04
Boundary for River Rch & Prof#=K159-00-00,K159-00-00_0004, 2
Up Type= 0
Dn Type= 3
Dn Slope=7.34253E-04
Boundary for River Rch & Prof#=K159-00-00,K159-00-00_0004, 3
Up Type= 0
Dn Type= 3
Dn Slope=7.34253E-04
Boundary for River Rch & Prof#=K159-00-00,K159-00-00_0004, 4
Up Type= 0
Dn Type= 3
Dn Slope=7.34253E-04
DSS Import GetInterval= 0
DSS Import GetPeak= 0
DSS Import FillOption= 0

--- K159-00-00.g01 (geometry) ---

Geom Title=K159-00-00 2012
Version=Version 3.0.1  Mar 2001

River Reach=K159-00-00      ,K159-00-00_0004
Reach XY= 30
      2999352.62      13923245.2      2999494.37      13923307.5
      2999910.14     13923599.62       3000056.3     13923636.16
      3000249.43     13923607.45      3000625.26     13923492.61
      3001046.25       13923309.      3001173.34     13923187.25
      3001379.53     13922738.35      3002000.75       13922111.
      3002272.23     13921890.26      3002818.63      13921625.7
       3003560.5       13921438.       3003592.5       13921392.
      3003607.25       13921038.      3003658.75       13920886.
      3003757.75       13920757.      3004219.25       13920542.
      3004336.25       13920445.       3004391.5       13920327.
        3004420.       13919661.      3004203.18     13919103.13
        3004196.       13918955.       3004242.6     13918747.78
      3004410.89     13918391.69      3004486.76     13918042.03
       3004534.3     13916384.63      3004643.47     13914167.03
      3004488.58     13912822.25      3004464.07      13912290.3

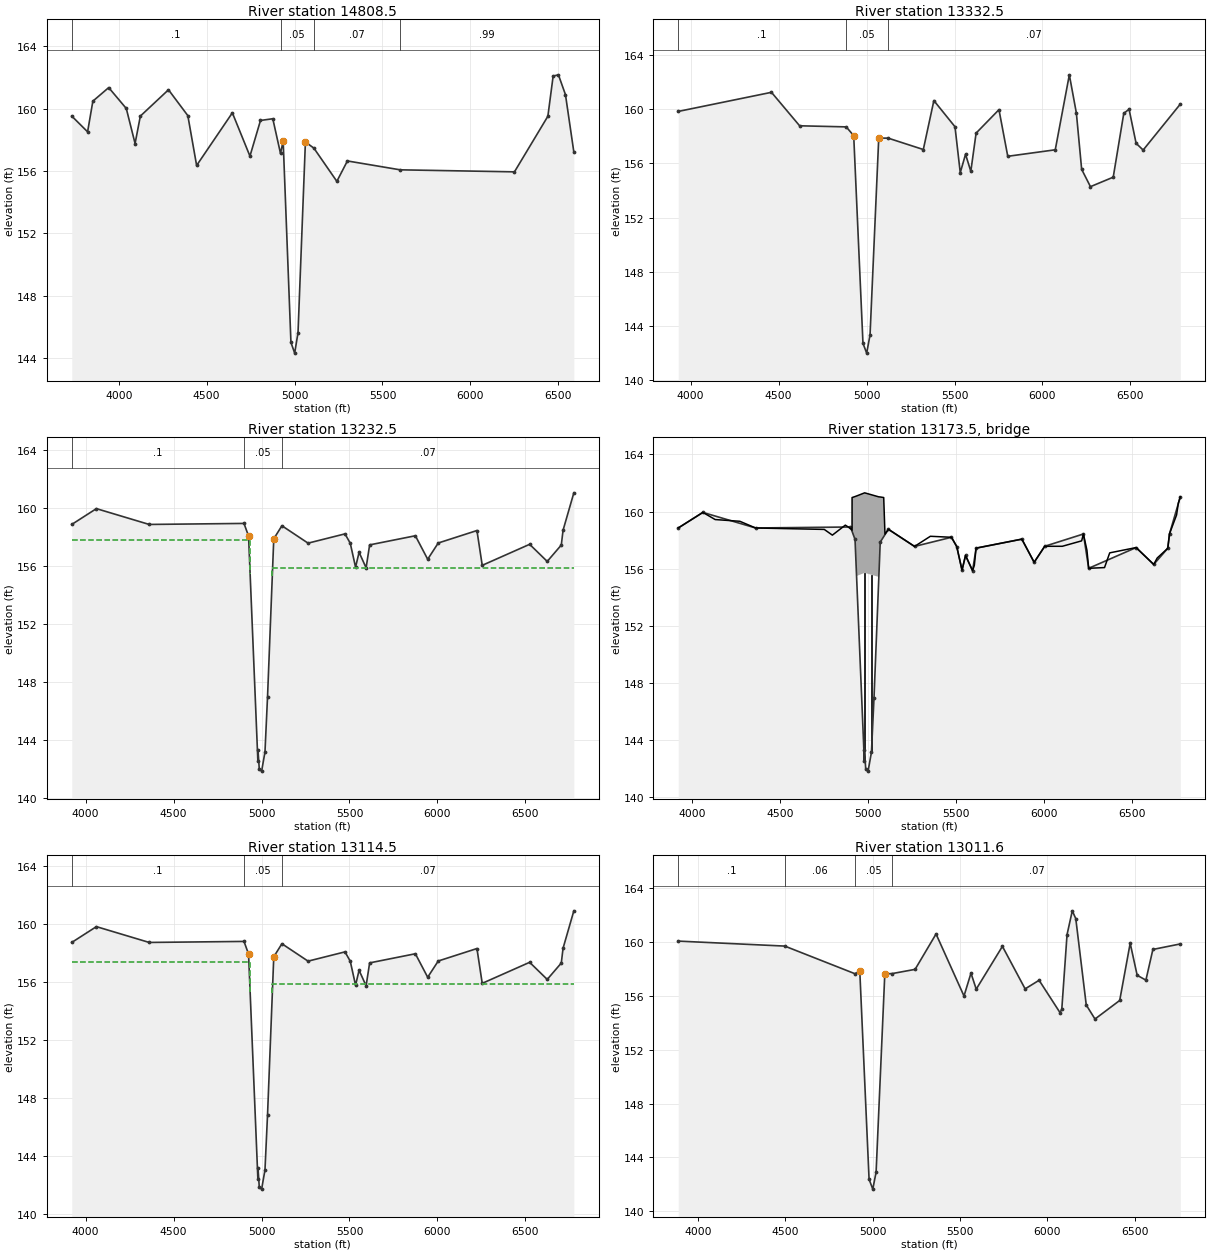
Type RM Length L Ch R = 1 ,14808.5 ,1527,1476,1429.7
BEGIN DESCRIPTION:
K159-00-00-X07
END DESCRIPTION:
XS GIS Cut Line= 5
      2999110.36      13924476.1      2999162.77      13923754.8
      2999323.87      13923352.1      2999405.14      13923125.8
      2999656.08      13921689.8
#Sta/Elev= 30
  3733.1  159.52  3823.1  158.51  3853.1  160.48  3943.1  161.35  4043.1  160.01
  4093.1  157.76  4123.1  159.52  4283.1  161.21  4393.1  159.55  4443.1  156.35
  4646.3  159.73  4746.3  156.95  4806.3  159.24  4876.3  159.35  4920.1  157.12
 4935.21  157.92  4979.4  144.99  5000.7   144.3  5019.7  145.62  5061.7  157.86
  5110.1  157.46  5240.5  155.33  5300.5  156.64  5600.5  156.07  6250.5  155.94
  6440.5  159.51  6470.5  162.09  6500.5  162.17  6540.5   160.9  6588.2  157.21
#Mann= 4 ,-1 , 0
  3733.1      .1       0  4920.1     .05       0  5110.1     .07       0
  5600.5     .99       0
Bank Sta=4935.21,5061.7
XS Rating Curve= 0
Exp/Cntr=.3,.1

Type RM Length L Ch R = 1 ,13332.5 ,102.7,100,99.8
BEGIN DESCRIPTION:
Mason Rd. - XS4
END DESCRIPTION:
XS GIS Cut Line= 5
      3000885.85     13924516.51      3000728.57     13923574.61
      3000670.41     13923343.66      3000230.91     13922163.34
      3000030.89      13921815.4
#Sta/Elev= 30
  3929.5  159.83  4459.5  161.24  4619.5  158.77  4884.4  158.69 4926.96  158.04
 4979.56  142.72  5000.7     142 5019.79  143.35 5069.19  157.86  5122.6  157.86
  5322.6  157.02  5382.6  160.63  5502.6   158.7  5532.6  155.31  5562.6  156.67
  5592.6  155.41  5622.6  158.23  5752.6  159.96  5802.6  156.52  6072.6     157
  6152.6  162.53  6192.6  159.71  6222.6  155.56  6272.6  154.28  6402.1  154.98
  6462.1  159.69  6492.1  159.99  6532.1  157.48  6572.1  156.98  6783.4  160.37
#Mann= 3 ,-1 , 0
  3929.5      .1       0  4884.4     .05       0  5122.6     .07       0
#XS Ineff= 2 , 0
       0 4835.29   157.8 5161.41       0  155.86
Permanent Ineff=
       F       F
Bank Sta=4926.96,5069.19
XS Rating Curve= 0
Exp/Cntr=.5,.3

Type RM Length L Ch R = 1 ,13232.5 ,116.5,118,118.5
BEGIN DESCRIPTION:
Mason Rd. - XS3
END DESCRIPTION:
XS GIS Cut Line= 5
        3000983.       13924486.      3000825.75     13923544.34
       3000767.6     13923313.39      3000328.09     13922133.07
      3000128.07     13921785.13
#Sta/Elev= 30
  3921.5  158.85  4061.5  159.94  4361.5  158.85  4900.5  158.92  4926.4  158.05
  4979.4  142.53    4980  143.32  4987.3  141.98  5000.7  141.84  5019.7  143.16
  5034.3  146.97  5069.7  157.86    5116  158.76  5264.7  157.56  5474.6   158.2
  5504.6  157.55  5534.6   155.9  5554.6  156.93  5594.6  155.86  5614.6  157.44
  5874.6  158.07  5944.6  156.45  6004.6  157.57  6224.6  158.43  6254.6  156.03
  6524.1  157.48  6624.1   156.3  6704.1  157.43  6714.1  158.45  6775.4  161.03
#Mann= 3 ,-1 , 0
  3921.5      .1       0  4900.5     .05       0    5116     .07       0
#XS Ineff= 2 , 0
       0 4935.29   157.8 5061.41       0  155.86
Permanent Ineff=
       F       F
Bank Sta=4926.4,5069.7
XS Rating Curve= 0
Exp/Cntr=.5,.3

Type RM Length L Ch R = 3 ,13173.5 ,,,
BEGIN DESCRIPTION:
MASON RD
Structure ID: K159-00-00-S11
END DESCRIPTION:
Bridge Culvert--1,0,-1,-1, 0
Deck Dist Width WeirC Skew NumUp NumDn MinLoCord MaxHiCord MaxSubmerge Is_Ogee
10,98,2.6,0, 49, 49, , , .95, 0, ,,,
  3921.5  4061.5  4131.5  4271.5  4361.5  4751.5  4797.6  4871.2  4900.5 4909.49
  4909.6  4926.4 4935.21 4935.33  4981.1    5061 5061.59  5061.7  5069.7  5089.5
 5096.59    5116  5264.7  5354.6  5474.6  5504.6  5534.6  5554.6  5594.6  5604.6
  5614.6  5874.6  5944.6  6004.6  6104.6  6214.6  6224.6  6244.6  6254.6  6344.6
  6374.1  6524.1  6624.1  6644.1  6704.1  6714.1  6754.1  6764.1  6775.4
  158.85  159.94  159.44  159.32  158.85  158.75  158.35  159.05  158.82  158.69
  160.98  161.05  161.09  161.09  161.31  161.03  161.03  161.03  161.02  160.98
  158.42  158.76  157.56  158.27   158.2  157.55   155.9  156.93  155.86  156.24
  157.44  158.07  156.45  157.57  157.57  157.95  158.43   157.3  156.03  156.08
  157.11  157.48   156.3  156.75  157.43  158.45  159.76  160.59  161.03
  158.85  159.94  159.44  159.32  158.85  158.75  158.35  159.05  158.82     158
     158     158     155  155.49  155.71  155.43     155     155     157     158
  158.42  158.76  157.56  158.27   158.2  157.55   155.9  156.93  155.86  156.24
  157.44  158.07  156.45  157.57  157.57  157.95  158.43   157.3  156.03  156.08
  157.11  157.48   156.3  156.75  157.43  158.45  159.76  160.59  161.03
  3921.5  4061.5  4131.5  4271.5  4361.5  4751.5  4797.6  4871.2  4900.5 4909.49
  4909.6  4926.4 4935.21 4935.33  4981.1    5061 5061.59  5061.7  5069.7  5089.5
 5096.59    5116  5264.7  5354.6  5474.6  5504.6  5534.6  5554.6  5594.6  5604.6
  5614.6  5874.6  5944.6  6004.6  6104.6  6214.6  6224.6  6244.6  6254.6  6344.6
  6374.1  6524.1  6624.1  6644.1  6704.1  6714.1  6754.1  6764.1  6775.4
  158.85  159.94  159.44  159.32  158.85  158.75  158.35  159.05  158.82  158.69
  160.98  161.05  161.09  161.09  161.31  161.03  161.03  161.03  161.02  160.98
  158.42  158.76  157.56  158.27   158.2  157.55   155.9  156.93  155.86  156.24
  157.44  158.07  156.45  157.57  157.57  157.95  158.43   157.3  156.03  156.08
  157.11  157.48   156.3  156.75  157.43  158.45  159.76  160.59  161.03
  158.75  159.84  159.34  159.22  158.75  158.65  158.25  158.95  158.72   157.9
   157.9   157.9   154.9  155.39  155.61  155.33   154.9   154.9   156.9   157.9
  158.32  158.66  157.46  158.17   158.1  157.45   155.8  156.83  155.76  156.14
  157.34  157.97  156.35  157.47  157.47  157.85  158.33   157.2  155.93  155.98
  157.01  157.38   156.2  156.65  157.33  158.35  159.66  160.49  160.93
Pier Skew, UpSta & Num, DnSta & Num=  ,4980, 2 ,4980, 2 , 0 , 0 , 0 ,,
     1.3     1.3
   141.6  156.71
     1.3     1.3
  141.55  156.66
Pier Skew, UpSta & Num, DnSta & Num=  ,5019.7, 2 ,5019.7, 2 , 0 , 0 , 0 ,,
     1.3     1.3
  142.13  156.57
     1.3     1.3
  142.08  156.52
BR Coef= 1 , 1 , 1 ,1.25, 0 ,,,.8,0,2,0,
WSPro=,,,, 1 ,,,, 0 ,,,, 0 ,,,,-1 ,-1 ,-1 , 0 , 0 , 0 , 0 , 0
BC Design=,, 0 ,, 0 ,,,,,,
BC HTab HWMax=161.03

Type RM Length L Ch R = 1 ,13114.5 ,100.9,102.9,106.5
BEGIN DESCRIPTION:
Mason Rd. - XS2
END DESCRIPTION:
XS GIS Cut Line= 5
       3001103.4       13924473.      3000933.74     13923506.95
      3000877.25     13923268.53      3000442.19     13922095.03
       3000343.8     13921710.45
#Sta/Elev= 30
  3921.5  158.75  4061.5  159.84  4361.5  158.75  4900.5  158.82  4926.4  157.95
  4979.4  142.43    4980  143.22  4987.3  141.88  5000.7  141.74  5019.7  143.06
  5034.3  146.87  5069.7  157.76    5116  158.66  5264.7  157.46  5474.6   158.1
  5504.6  157.45  5534.6   155.8  5554.6  156.83  5594.6  155.76  5614.6  157.34
  5874.6  157.97  5944.6  156.35  6004.6  157.47  6224.6  158.33  6254.6  155.93
  6524.1  157.38  6624.1   156.2  6704.1  157.33  6714.1  158.35  6775.4  160.93
#Mann= 3 ,-1 , 0
  3921.5      .1       0  4900.5     .05       0    5116     .07       0
#XS Ineff= 2 , 0
       0 4935.25   157.4  5061.5       0  155.86
Permanent Ineff=
       F       F
Bank Sta=4926.4,5069.7
XS Rating Curve= 0
Exp/Cntr=.5,.3

Type RM Length L Ch R = 1 ,13011.6 ,1185.8,1140.9,1088.6
BEGIN DESCRIPTION:
Mason Rd. - XS1
END DESCRIPTION:
XS GIS Cut Line= 5
      3001194.29      13924430.2      3001024.55     13923463.94
      3000968.06     13923225.52        3000533.     13922052.02
      3000434.61     13921667.43
#Sta/Elev= 30
  3886.7  160.07  4496.7   159.7  4897.8  157.65 4926.26  157.82 4979.34  142.37
 5000.68  141.64  5019.6  142.91 5069.39  157.63  5112.8  157.66  5242.8  157.97
  5362.8   160.6  5522.8  155.99  5562.8  157.69  5592.8   156.5  5742.8  159.68
  5872.8  156.52  5952.8  157.16  6072.8  154.75  6082.8  155.02  6112.8  160.55
  6142.8  162.32  6162.8  161.74  6222.8  155.32  6272.8  154.28  6414.3  155.66
  6474.3  159.91  6514.3  157.53  6564.3  157.17  6604.3  159.45  6761.3  159.86
#Mann= 4 ,-1 , 0
  3886.7      .1       0  4496.7     .06       0  4897.8     .05       0
  5112.8     .07       0
#XS Ineff= 2 , 0
       0 4835.25   157.4  5161.5       0  155.86
Permanent Ineff=
       F       F
Bank Sta=4926.26,5069.39
XS Rating Curve= 0
Exp/Cntr=.3,.1

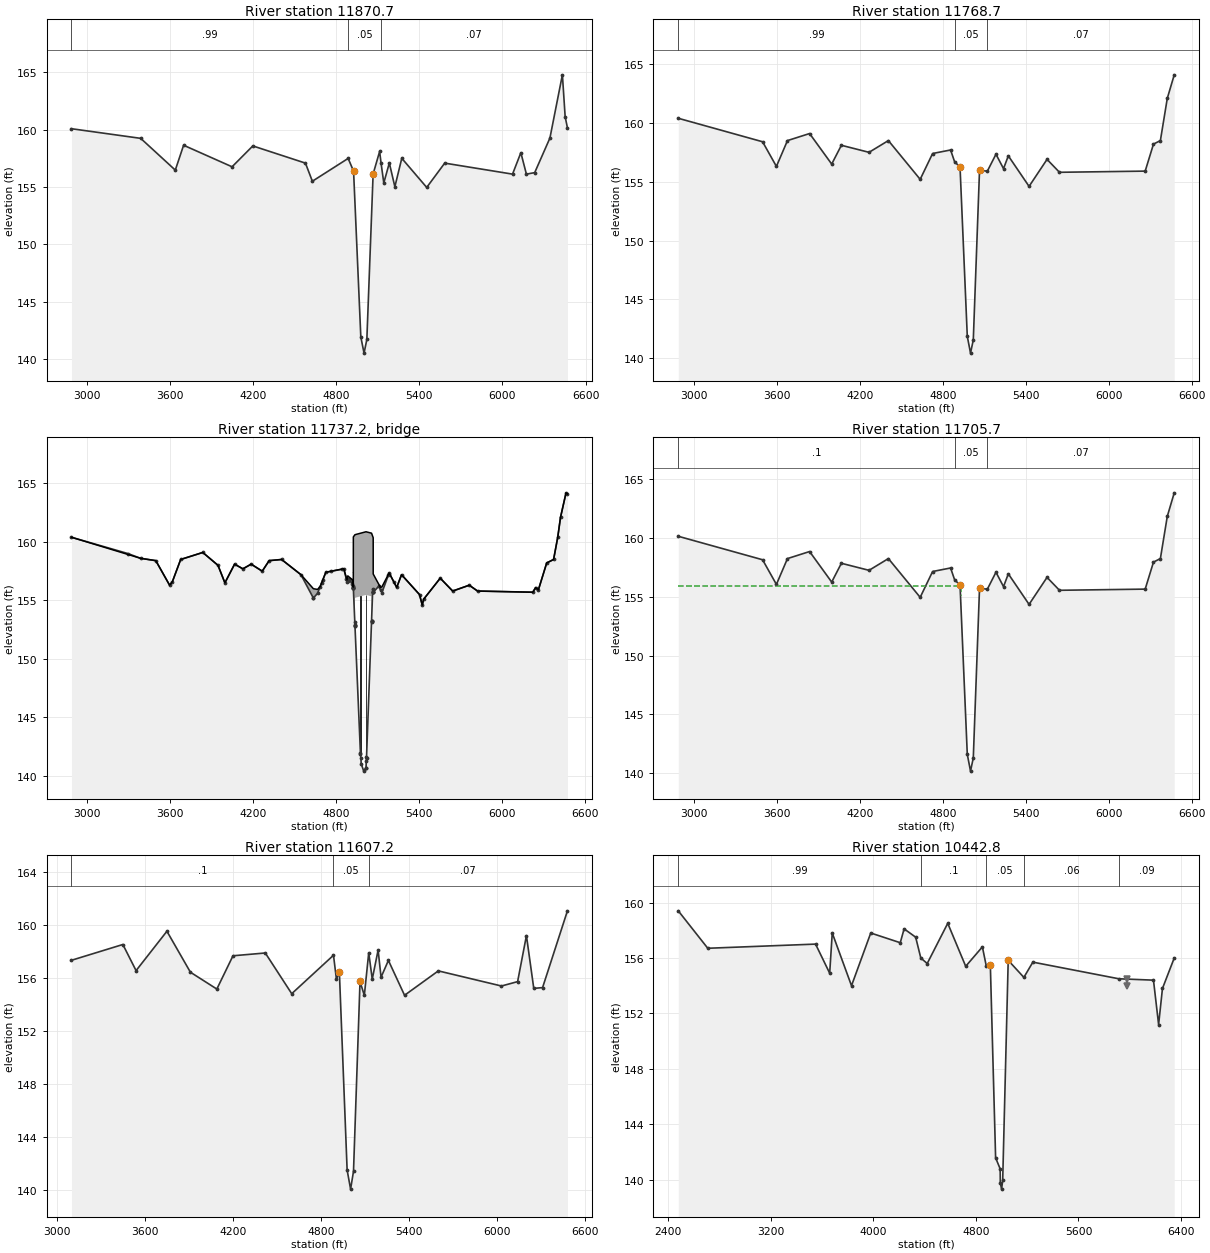
Type RM Length L Ch R = 1 ,11870.7 ,101.5,102,102.1
BEGIN DESCRIPTION:
Carolina Oaks - XS4
END DESCRIPTION:
XS GIS Cut Line= 4
       3001294.5     13924469.24       3001767.2     13922537.74
      3001588.32     13922381.66      3000585.03     13921468.75
#Sta/Elev= 30
  2887.1  160.08  3387.1  159.24  3637.1  156.47  3697.1  158.64  4047.1  156.76
  4197.1  158.58  4577.1  157.08  4627.1   155.5  4885.6  157.49 4924.74  156.38
 4977.06  141.92 5000.42  140.51 5020.61   141.7 5065.91  156.13    5113   158.1
    5123  157.11    5143  155.35    5183  157.09    5223  155.02    5273   157.5
    5453  154.96    5583  157.08    6073  156.12    6133  157.99    6173  156.12
    6233  156.25    6343  159.27    6433  164.78    6453  161.12  6469.5  160.16
#Mann= 3 ,-1 , 0
  2887.1     .99       0  4885.6     .05       0    5123     .07       0
#XS Ineff= 2 , 0
       0  4824.6  155.94  5165.6       0   154.6
Permanent Ineff=
       F       F
Bank Sta=4924.74,5065.91
XS Rating Curve= 0
Exp/Cntr=.5,.3

Type RM Length L Ch R = 1 ,11768.7 ,62.9,63,63.1
BEGIN DESCRIPTION:
Carolina Oaks - XS3
END DESCRIPTION:
XS GIS Cut Line= 4
      3001364.78       13924396.      3001837.77     13922452.34
       3001660.4      13922326.7      3000655.31     13921395.51
#Sta/Elev= 30
  2886.2  160.41  3496.2  158.41  3596.2  156.31  3676.2  158.51  3836.2  159.11
  3996.2  156.51  4066.2  158.11  4266.2  157.51  4406.2  158.51  4636.2  155.21
  4726.2  157.41  4856.2  157.71  4885.2  156.71  4924.6  156.25    4977  141.84
  5000.4  140.41  5020.5  141.54  5065.6     156  5121.9   155.9  5184.5  157.35
  5239.1  156.12  5273.9  157.21  5423.9  154.61  5553.9  156.91  5643.9  155.81
  6263.9  155.91  6323.9  158.21  6373.9  158.51  6423.9  162.11  6474.1  164.11
#Mann= 3 ,-1 , 0
  2886.2     .99       0  4885.2     .05       0  5121.9     .07       0
#XS Ineff= 2 , 0
       0  4924.6  155.94  5065.6       0   154.6
Permanent Ineff=
       F       F
Bank Sta=4924.6,5065.6
XS Rating Curve= 0
Exp/Cntr=.5,.3

Type RM Length L Ch R = 3 ,11737.2 ,,,
BEGIN DESCRIPTION:
CAROLINA OAKS
Structure ID: K159-00-00-S8
END DESCRIPTION:
Bridge Culvert--1,0,-1,-1, 0
Deck Dist Width WeirC Skew NumUp NumDn MinLoCord MaxHiCord MaxSubmerge Is_Ogee
10,41,2.6,0, 60, 60, , , .95, 0, ,,,
  2886.2  3386.2  3496.2  3596.2  3616.2  3676.2  3836.2  3946.2  3996.2  4066.2
  4126.2  4186.2  4266.2  4316.2  4406.2  4546.2  4636.2  4666.2  4685.2  4726.2
  4856.2  4879.4  4885.2  4893.7  4915.2    4925  4925.1 4925.19  4925.3 4936.91
    4937  5016.9 5056.89    5057  5065.6  5068.9 5069.01  5089.9  5107.9  5121.9
    5132  5184.5  5239.1  5273.9  5403.9  5423.9  5433.9  5553.9  5643.9  5763.9
  5823.9  6223.9  6243.9  6263.9  6323.9  6373.9  6403.9  6423.9  6463.9  6474.1
   160.4   158.6   158.4   156.3   156.6   158.5   159.1     158   156.5   158.1
   157.7   158.1   157.5   158.4   158.5   157.2     156  155.94  156.18  157.41
  157.71  156.75   157.1  157.01   156.8  156.14  157.33  157.33  160.43  160.62
  160.62  160.87  160.75  160.75  160.47  160.36  157.26   156.8  156.41   156.1
  156.16  157.35  156.11   157.2   155.5   154.6   155.1   156.9   155.8   156.3
   155.8   155.7   156.1   155.9   158.2   158.5   160.4   162.1   164.2   164.1
   160.4   158.6   158.4   156.3   156.6   158.5   159.1     158   156.5   158.1
   157.7   158.1   157.5   158.4   158.5   157.2   155.2   155.6  156.17   157.4
   157.7   156.6   156.7  156.84  156.42  156.13   156.1  156.08  156.05  152.86
  155.22  155.47  155.35  153.23  155.99   155.7  155.69  153.87   156.2  155.89
  155.67  157.34  156.11   157.2   155.5   154.6   155.1   156.9   155.8   156.3
   155.8   155.7   156.1   155.9   158.2   158.5   160.4   162.1   164.2   164.1
  2886.2  3386.2  3496.2  3596.2  3616.2  3676.2  3836.2  3946.2  3996.2  4066.2
  4126.2  4186.2  4266.2  4316.2  4406.2  4546.2  4636.2  4666.2  4685.2  4726.2
  4856.2  4879.4  4885.2  4893.7  4915.2    4925  4925.1 4925.19  4925.3 4936.91
    4937  5016.9 5056.89    5057  5065.6  5068.9 5069.01  5089.9  5107.9  5121.9
    5132  5184.5  5239.1  5273.9  5403.9  5423.9  5433.9  5553.9  5643.9  5763.9
  5823.9  6223.9  6243.9  6263.9  6323.9  6373.9  6403.9  6423.9  6463.9  6474.1
   160.4   158.6   158.4   156.3   156.6   158.5   159.1     158   156.5   158.1
   157.7   158.1   157.5   158.4   158.5   157.2     156  155.94  156.18  157.41
  157.71  156.75   157.1  157.01   156.8  156.14  157.33  157.33  160.43  160.62
  160.62  160.87  160.75  160.75  160.47  160.36  157.26   156.8  156.41   156.1
  156.16  157.35  156.11   157.2   155.5   154.6   155.1   156.9   155.8   156.3
   155.8   155.7   156.1   155.9   158.2   158.5   160.4   162.1   164.2   164.1
  160.17  158.37  158.17  156.07  156.37  158.27  158.87  157.77  156.27  157.87
  157.47  157.87  157.27  158.17  158.27  156.97  154.97  155.37  155.94  157.17
  157.47  156.37  156.47  156.61  156.19   155.9  155.87  155.85  155.82  152.63
  154.99  155.24  155.12     153  155.76  155.47  155.46  153.64  155.97  155.66
  155.44  157.11  155.88  156.97  155.27  154.37  154.87  156.67  155.57  156.07
  155.57  155.47  155.87  155.67  157.97  158.27  160.17  161.87  163.97  163.87
Pier Skew, UpSta & Num, DnSta & Num=  ,4977, 2 ,4977, 2 , 0 , 0 , 0 ,,
     1.4     1.4
  140.76  156.35
     1.4     1.4
  140.53  156.12
Pier Skew, UpSta & Num, DnSta & Num=  ,5016.9, 2 ,5016.9, 2 , 0 , 0 , 0 ,,
     1.4     1.4
  139.68  156.47
     1.4     1.4
  139.45  156.24
BR Coef= 1 , 1 , 1 ,1.25, 0 ,,,.8,0,2,0,
WSPro=,,,, 1 ,,,, 0 ,,,, 0 ,,,,-1 ,-1 ,-1 , 0 , 0 , 0 , 0 , 0
BR U #Sta/Elev= 87
  2886.2   160.4  3296.2     159  3386.2   158.6  3496.2   158.4  3596.2   156.3
  3616.2   156.6  3676.2   158.5  3836.2   159.1  3946.2     158  3996.2   156.5
  4066.2   158.1  4126.2   157.7  4186.2   158.1  4266.2   157.5  4316.2   158.4
  4406.2   158.5  4546.2   157.2  4635.2  155.22  4636.2   155.2  4666.2   155.6
  4685.2  156.17  4695.2  156.47  4705.2  156.77  4726.2   157.4  4765.2  157.49
  4845.2  157.67  4856.2   157.7  4875.2   156.8  4879.4   156.6  4885.2   156.7
  4893.7  156.84  4915.2  156.42  4924.6  156.24    4925  156.13  4925.1   156.1
 4925.19  156.08  4925.3  156.05 4925.41  156.02  4935.8  153.16  4936.8  152.89
 4936.91  152.86    4937  152.83  4937.1  152.81  4976.5  141.98    4977  141.83
  4980.3  141.49  4982.1  141.03  5000.4   140.4  5016.8  140.69  5016.9  140.69
  5018.8  141.24  5019.7  141.57  5020.5  141.53  5056.8  153.17 5056.89   153.2
    5057  153.23  5057.1  153.26  5065.6  155.99  5068.7  155.72 5068.79  155.71
  5068.9   155.7 5069.01  155.69  5107.9   156.2  5121.9  155.89    5132  155.67
  5178.1  157.14  5182.9  157.29  5184.5  157.34  5217.2   156.6  5239.1  156.11
  5273.9   157.2  5403.9   155.5  5423.9   154.6  5433.9   155.1  5553.9   156.9
  5643.9   155.8  5763.9   156.3  5823.9   155.8  6223.9   155.7  6243.9   156.1
  6263.9   155.9  6323.9   158.2  6373.9   158.5  6403.9   160.4  6423.9   162.1
  6463.9   164.2  6474.1   164.1
BR U #Mann= 3
  2886.2      .1  4885.2     .05 5068.79     .07
BR U Banks=4924.6,5065.6
BR D #Sta/Elev= 87
  2886.2  160.17  3296.2  158.77  3386.2  158.37  3496.2  158.17  3596.2  156.07
  3616.2  156.37  3676.2  158.27  3836.2  158.87  3946.2  157.77  3996.2  156.27
  4066.2  157.87  4126.2  157.47  4186.2  157.87  4266.2  157.27  4316.2  158.17
  4406.2  158.27  4546.2  156.97  4635.2  154.99  4636.2  154.97  4666.2  155.37
  4685.2  155.94  4695.2  156.24  4705.2  156.54  4726.2  157.17  4765.2  157.26
  4845.2  157.44  4856.2  157.47  4875.2  156.57  4879.4  156.37  4885.2  156.47
  4893.7  156.61  4915.2  156.19  4924.6  156.01    4925   155.9  4925.1  155.87
 4925.19  155.85  4925.3  155.82 4925.41  155.79  4935.8  152.93  4936.8  152.66
 4936.91  152.63    4937   152.6  4937.1  152.58  4976.5  141.75    4977   141.6
  4980.3  141.26  4982.1   140.8  5000.4  140.17  5016.8  140.46  5016.9  140.46
  5018.8  141.01  5019.7  141.34  5020.5   141.3  5056.8  152.94 5056.89  152.97
    5057     153  5057.1  153.03  5065.6  155.76  5068.7  155.49 5068.79  155.48
  5068.9  155.47 5069.01  155.46  5107.9  155.97  5121.9  155.66    5132  155.44
  5178.1  156.91  5182.9  157.06  5184.5  157.11  5217.2  156.37  5239.1  155.88
  5273.9  156.97  5403.9  155.27  5423.9  154.37  5433.9  154.87  5553.9  156.67
  5643.9  155.57  5763.9  156.07  5823.9  155.57  6223.9  155.47  6243.9  155.87
  6263.9  155.67  6323.9  157.97  6373.9  158.27  6403.9  160.17  6423.9  161.87
  6463.9  163.97  6474.1  163.87
BR D #Mann= 3
  2886.2      .1  4885.2     .05 5068.79     .07
BR D Banks=4924.6,5065.6
BC Design=,, 0 ,, 0 ,,,,,,
BC HTab HWMax=164.21

Type RM Length L Ch R = 1 ,11705.7 ,98.3,98.5,98.6
BEGIN DESCRIPTION:
Carolina Oaks - XS2
END DESCRIPTION:
XS GIS Cut Line= 4
       3001410.3      13924354.1      3001887.65     13922424.97
      3001696.61     13922257.75      3000699.36     13921348.77
#Sta/Elev= 30
  2886.2  160.16  3496.2  158.16  3596.2  156.06  3676.2  158.26  3836.2  158.86
  3996.2  156.26  4066.2  157.86  4266.2  157.26  4406.2  158.26  4636.2  154.96
  4726.2  157.16  4856.2  157.46  4885.2  156.46  4924.6     156    4977  141.59
  5000.4  140.16  5020.5  141.29  5065.6  155.75  5121.9  155.65  5184.5   157.1
  5239.1  155.87  5273.9  156.96  5423.9  154.36  5553.9  156.66  5643.9  155.56
  6263.9  155.66  6323.9  157.96  6373.9  158.26  6423.9  161.86  6474.1  163.86
#Mann= 3 ,-1 , 0
  2886.2      .1       0  4885.2     .05       0  5121.9     .07       0
#XS Ineff= 2 , 0
       0 4927.93  155.94 5062.27       0   154.6
Permanent Ineff=
       F       F
Bank Sta=4924.6,5065.6
XS Rating Curve= 0
Exp/Cntr=.5,.3

Type RM Length L Ch R = 1 ,11607.2 ,1124.1,1164.4,1196.9
BEGIN DESCRIPTION:
Carolina Oaks - XS1
END DESCRIPTION:
XS GIS Cut Line= 4
      3001525.81     13924072.67      3001952.02     13922350.26
      3001760.97     13922183.03      3000763.72     13921274.05
#Sta/Elev= 30
  3099.5  157.36  3449.5  158.55  3539.5  156.58  3749.5  159.55  3909.5  156.46
  4089.5  155.19  4199.5   157.7  4419.5  157.91  4599.5  154.84  4883.9  157.74
  4903.9  155.93  4923.9  156.48 4976.74  141.54 5000.42   140.1  5020.2  141.45
 5064.57  155.76  5093.9  154.71  5123.9  157.93  5147.8  155.94  5187.8  158.13
  5207.8  156.08  5257.8  157.35  5367.8  154.72  5597.8  156.56  6027.8  155.42
  6137.8  155.75  6197.8  159.22  6247.8  155.24  6307.8   155.3  6477.1  161.09
#Mann= 3 ,-1 , 0
  3099.5      .1       0  4883.9     .05       0  5123.9     .07       0
#XS Ineff= 2 , 0
       0 4827.93  155.94 5162.27       0   154.6
Permanent Ineff=
       F       F
Bank Sta=4923.9,5064.57
XS Rating Curve= 0
Exp/Cntr=.3,.1

Type RM Length L Ch R = 1 ,10442.8 ,222.3,220.2,220
BEGIN DESCRIPTION:
Cross Section K159-00-00-X6A
The levee set on the right overbank at station 6000 is used to isolate the far ROB ditch and is not intended as a certified flood-control levee.
END DESCRIPTION:
XS GIS Cut Line= 4
       3003343.8       13924088.      3002863.45     13921760.68
      3002782.15     13921538.96      3002294.39     13920386.07
#Sta/Elev= 30
  2481.2   159.4  2711.2   156.7  3551.2     157  3661.2   154.9  3681.2   157.8
  3831.2     154  3981.2   157.8  4211.2   157.1  4241.2   158.1  4331.2   157.5
  4371.2     156  4421.2   155.6  4581.2   158.5  4721.2   155.4  4851.2   156.8
  4881.2  155.43  4913.2  155.46  4954.2  141.59  4989.7  140.79  4990.7  139.79
  5000.7  139.33  5009.4  139.96  5052.4  155.83  5174.4   154.6  5244.4   155.7
  5914.4   154.5  6184.4   154.4  6224.4   151.2  6254.4   153.8  6346.2     156
#Mann= 5 ,-1 , 0
  2481.2     .99       0  4371.2      .1       0  4881.2     .05       0
  5174.4     .06       0  5914.4     .09       0
Levee=0,,,-1,5974.4,154,,
Bank Sta=4913.2,5052.4
XS Rating Curve= 0
Exp/Cntr=.3,.1

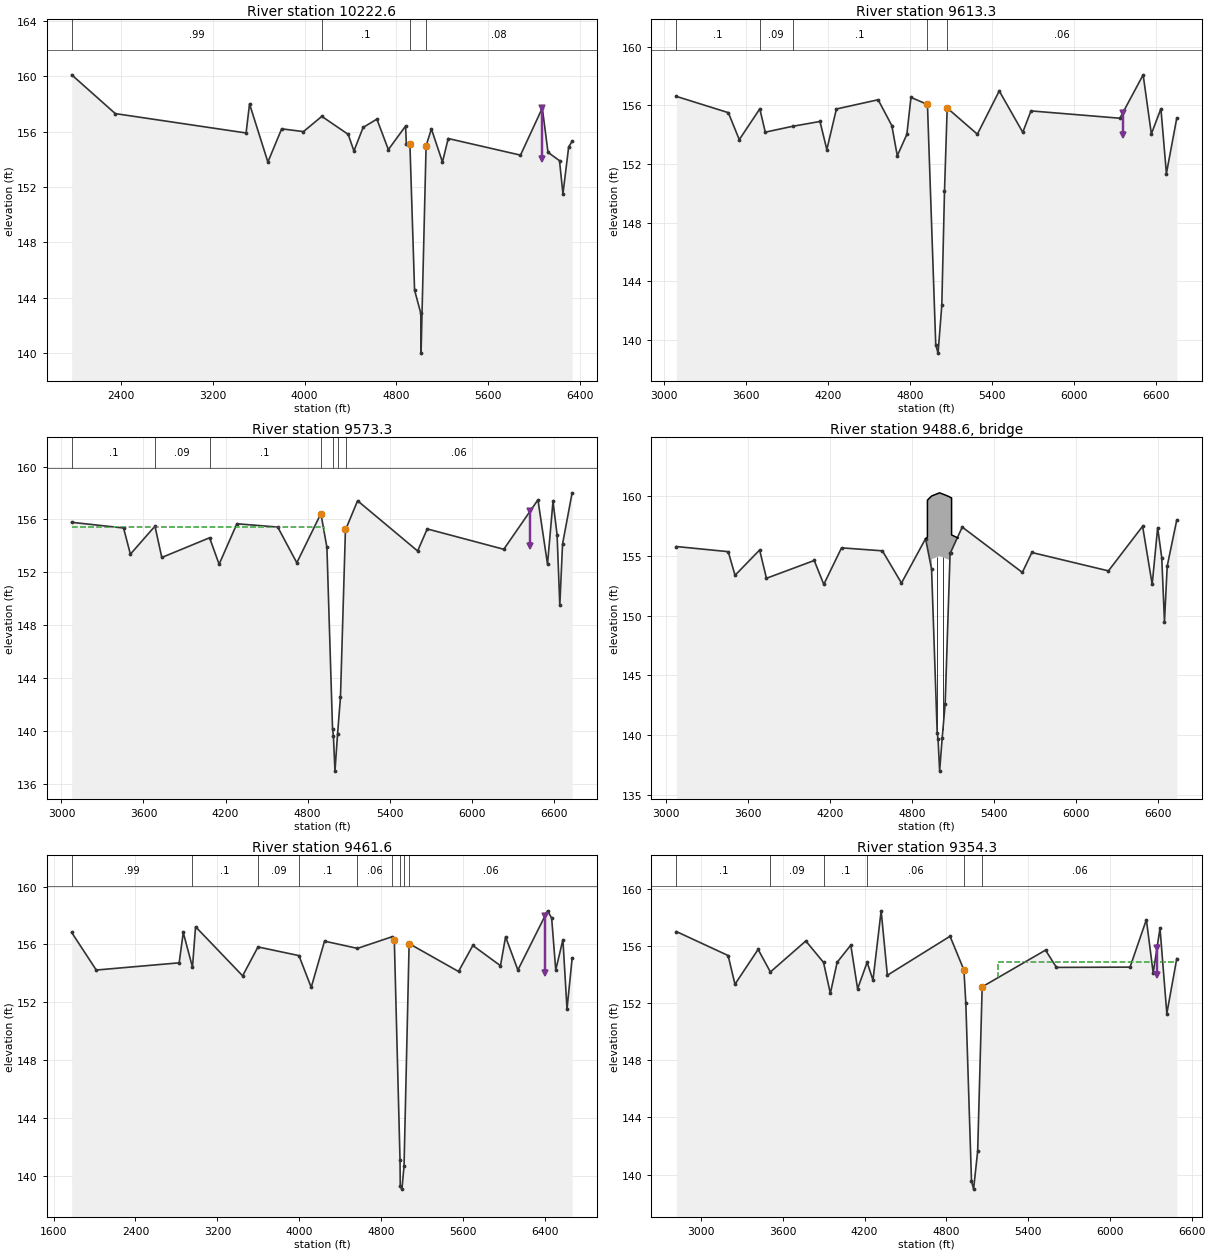
Type RM Length L Ch R = 1 ,10222.6 ,696.3,609.3,521.3
BEGIN DESCRIPTION:
Cross Section K159-00-00-X6
The levee set on the right overbank at station 6000 is used to isolate the far ROB ditch and is not intended as a certified flood-control levee.
END DESCRIPTION:
XS GIS Cut Line= 4
      3004186.32     13924362.09      3003037.69     13921596.48
      3003010.55     13921524.45      3002601.17      13920301.2
#Sta/Elev= 30
  1969.3   160.1  2349.3   157.3  3489.3   155.9  3519.3     158  3679.3   153.8
  3799.3   156.2  3989.3     156  4149.3   157.1  4379.3   155.8  4429.3   154.6
  4509.3   156.3  4629.3   156.9  4729.3   154.7  4879.3   156.4  4886.2  155.12
  4917.1  155.12  4957.7  144.55    5012  142.88  5014.3     140  5058.2  154.98
  5104.5  156.19  5200.9   153.8  5250.9   155.5  5880.9   154.3  6070.9   157.7
  6120.9   154.5  6220.9   153.9  6250.9   151.5  6300.9   154.9  6330.9   155.3
#Mann= 4 ,-1 , 0
  1969.3     .99       0  4149.3      .1       0  4917.1     .05       0
  5058.2     .08       0
Levee=0,,,-1,6070.9,154,,
Bank Sta=4917.1,5058.2
XS Rating Curve= 0
Exp/Cntr=.3,.1

Type RM Length L Ch R = 1 ,9613.3  ,39.71,40,44.5
BEGIN DESCRIPTION:
Cypresswood - XS4
END DESCRIPTION:
XS GIS Cut Line= 6
      3004825.43     13922464.11      3004286.11     13921375.34
      3003709.62     13921388.29      3003450.96     13921388.29
      3003029.71     13921410.46      3002682.93     13920276.36
#Sta/Elev= 30
  3091.4  156.61  3471.4   155.5  3551.4  153.66  3701.4  155.76  3741.4  154.17
  3941.4  154.57  4141.4   154.9  4191.4  152.98  4261.4  155.75  4566.4  156.38
  4666.4  154.62  4706.4  152.56  4776.4  154.02  4806.4  156.54 4926.92  156.06
 4987.59  139.66 5004.48   139.1 5031.78  142.36  5051.5  150.13 5071.13  155.82
  5291.7  154.03  5451.7  156.98  5623.6  154.16  5683.6  155.62  6333.6  155.12
  6503.6  158.08  6563.6  154.05  6633.6  155.77  6673.6  151.35  6749.5  155.13
#Mann= 5 ,-1 , 0
  3091.4      .1       0  3701.4     .09       0  3941.4      .1       0
 4926.92     .04       0 5071.13     .06       0
Levee=0,,,-1,6354.522,154,,
#XS Ineff= 2 , 0
       0  4818.5  155.43  5183.2       0  154.86
Permanent Ineff=
       F       F
Bank Sta=4926.92,5071.13
XS Rating Curve= 0
Exp/Cntr=.5,.3

Type RM Length L Ch R = 1 ,9573.3  ,110.79,111.7,119.9
BEGIN DESCRIPTION:
XS 9573.3 - Cypresswood - Added by RGME
END DESCRIPTION:
XS GIS Cut Line= 6
      3004834.4713922449.3179269 3004284.328483313921329.8231388
 3003712.737765313921342.3266857 3003453.735721313921345.8991277
 3003023.256461813921363.7613377 3002686.3115144 13920263.979267
#Sta/Elev= 30
    3075  155.78  3454.3  155.35  3504.2  153.37  3683.9  155.49  3733.8  153.12
  4083.1  154.61    4153  152.61  4282.8  155.67  4581.5  155.42  4720.9  152.72
  4897.2  156.44  4941.1  153.88  4982.2  140.17  4988.6  139.62    5000  136.96
  5018.7  139.75  5040.2  142.56  5076.6  155.24  5079.6  155.27  5165.3  157.41
  5604.5  153.61  5674.4  155.28  6234.2  153.74    6484  157.48    6554  152.61
    6594  157.36  6623.9  154.85  6643.9  149.49  6663.9  154.14  6733.9  158.01
#Mann= 7 ,-1 , 0
    3075      .1       0  3683.9     .09       0  4083.1      .1       0
  4897.2    .013       0  4988.6     .04       0  5018.7    .013       0
  5079.6     .06       0
Levee=0,,,-1,6429.52,154,,
#XS Ineff= 2 , 0
       0 4921.83  155.43 5079.87       0  154.86
Permanent Ineff=
       F       F
Bank Sta=4897.2,5076.6
XS Rating Curve= 0
Exp/Cntr=.5,.3

Type RM Length L Ch R = 3 ,9488.6  ,,,
BEGIN DESCRIPTION:
CYPRESSWOOD
Structure ID: K159-00-00-S07
END DESCRIPTION:
Bridge Culvert--1,0,-1,-1, 0
Deck Dist Width WeirC Skew NumUp NumDn MinLoCord MaxHiCord MaxSubmerge Is_Ogee
10,95,2.6,0, 31, 29, , , .95, 0, ,,,
  4897.2  4904.5 4910.69  4910.8 4910.91  4928.5  4943.2 4943.31  4943.4  4943.5
  4960.1  4983.4  4984.3  4986.5  4986.7  4999.8  5002.9  5012.6  5013.3  5023.6
  5031.7  5052.5  5063.5  5063.6 5068.49  5068.6  5073.2 5087.19  5087.3 5087.41
  5135.8
  156.44   156.5  156.57  159.67  159.67  159.87  160.03  160.03  160.03  160.03
   160.1  160.21  160.21  160.22  160.22  160.28  160.27  160.22  160.22  160.17
  160.14  160.04  159.99  159.99  159.96  159.96  159.93  159.85  159.85  156.75
  156.49
                                                  152.05  152.02  154.73  154.73
   154.8  154.91  154.91  154.92  154.92  154.98  154.97  154.92  154.92  154.87
  154.84  154.74  154.69  154.69  154.66  154.61  154.61  154.61  154.61
        
 4910.91  4928.5  4943.2 4943.31  4943.4  4943.5  4960.1  4983.4  4984.3  4986.5
  4986.7  4999.8  5002.9  5012.6  5013.3  5023.6  5031.7  5052.5  5063.5  5063.6
 5068.49  5068.6  5073.2 5087.19  5087.3 5087.41  5135.8  5162.5  5183.7
  159.67  159.87  160.03  160.03  160.03  160.03   160.1  160.21  160.21  160.22
  160.22  160.28  160.27  160.22  160.22  160.17  160.14  160.04  159.99  159.99
  159.96  159.96  159.93  159.85  159.85  156.75  156.49  156.73  156.42
          156.19  152.05  152.02  154.73  154.73   154.8  154.91  154.91  154.92
  154.92  154.98  154.97  154.92  154.92  154.87  154.84  154.74  154.69  154.69
  154.66  154.61  154.61  154.61  154.61
Pier Skew, UpSta & Num, DnSta & Num=  ,4983.4, 2 ,4983.4, 2 , 0 , 0 , 0 ,,
     1.2     1.2
  138.01  155.91
     1.2     1.2
  138.15  156.05
Pier Skew, UpSta & Num, DnSta & Num=  ,5023.6, 2 ,5023.6, 2 , 0 , 0 , 0 ,,
     1.2     1.2
  139.49  155.87
     1.2     1.2
  139.63  156.01
BR Coef= 1 , 1 , 1 ,1.25, 0 ,,,.8,0,2,0,
WSPro=,,,, 1 ,,,, 0 ,,,, 0 ,,,,-1 ,-1 ,-1 , 0 , 0 , 0 , 0 , 0
BC Design=,, 0 ,, 0 ,,,,,,
BC HTab HWMax=158.22

Type RM Length L Ch R = 1 ,9461.6  ,100.3,107.3,100.3
BEGIN DESCRIPTION:
Cypresswood - XS2
The levee set on the right overbank at station 6400 is used to isolate the far ROB ditch and is not intended as a certified flood-control levee.
END DESCRIPTION:
XS GIS Cut Line= 6
      3005435.94      13923470.4      3004297.96      13921216.9
      3003718.37     13921229.92      3003459.63     13921229.92
      3003069.94     13921250.43      3002776.58      13920231.2
#Sta/Elev= 30
  1776.7  156.83  2016.7  154.23  2826.7  154.73  2866.7  156.83  2956.7  154.43
  2986.7  157.23  3446.7  153.83  3596.7  155.83  3996.7  155.23  4116.7  153.03
  4246.7  156.23  4568.5  155.73  4904.5  156.53  4928.5  156.32  4984.3  141.07
  4986.7  139.25  5002.9  139.06  5023.6  140.67  5073.2  156.06  5555.6  154.13
  5695.6  155.93  5965.6  154.53  6015.6  156.53  6135.6  154.23  6425.6  158.33
  6465.6  157.83  6505.6  154.23  6575.6  156.33  6615.6  151.53  6665.6  155.03
#Mann= 9 ,-1 , 0
  1776.7     .99       0  2956.7      .1       0  3596.7     .09       0
  3996.7      .1       0  4568.5     .06       0  4904.5     .03       0
  4984.3     .04       0  5023.6     .03       0  5073.2     .06       0
Levee=0,,,-1,6400,154,,
#XS Ineff= 2 , 0
       0 4921.83   155.2 5079.87       0  154.86
Permanent Ineff=
       F       F
Bank Sta=4928.5,5073.2
XS Rating Curve= 0
Exp/Cntr=.5,.3

Type RM Length L Ch R = 1 ,9354.3  ,528.9,612.3,694.6
BEGIN DESCRIPTION:
Cypresswood - XS1
END DESCRIPTION:
XS GIS Cut Line= 6
      3004977.45     13922456.98      3004345.46     13921193.38
      3004232.69     13921118.26      3003462.34     13921129.76
      3003072.65     13921150.27      3002806.27     13920224.83
#Sta/Elev= 30
  2818.9  157.01  3198.9  155.33  3248.9  153.32  3418.9  155.76  3508.9  154.18
  3768.9  156.35  3898.9  154.85  3948.9  152.68  3998.9  154.86  4098.9  156.06
  4148.9     153  4218.9  154.86  4261.7  153.61  4321.7  158.46  4367.2  153.95
  4827.2  156.68    4929  154.32 4943.09  151.98 4984.55  139.56 4999.99  138.98
 5029.94  141.64    5063  153.14  5527.9  155.71  5607.9   154.5  6147.9  154.52
  6267.9  157.84  6317.9  154.11  6367.9  157.24  6417.9  151.27    6491  155.12
#Mann= 6 ,-1 , 0
  2818.9      .1       0  3508.9     .09       0  3898.9      .1       0
  4218.9     .06       0    4929     .04       0    5063     .06       0
Levee=0,,,-1,6345.425,154,,
#XS Ineff= 2 , 0
       0 4821.83   155.2 5179.87       0  154.86
Permanent Ineff=
       F       F
Bank Sta=4929,5063
XS Rating Curve= 0
Exp/Cntr=.3,.1