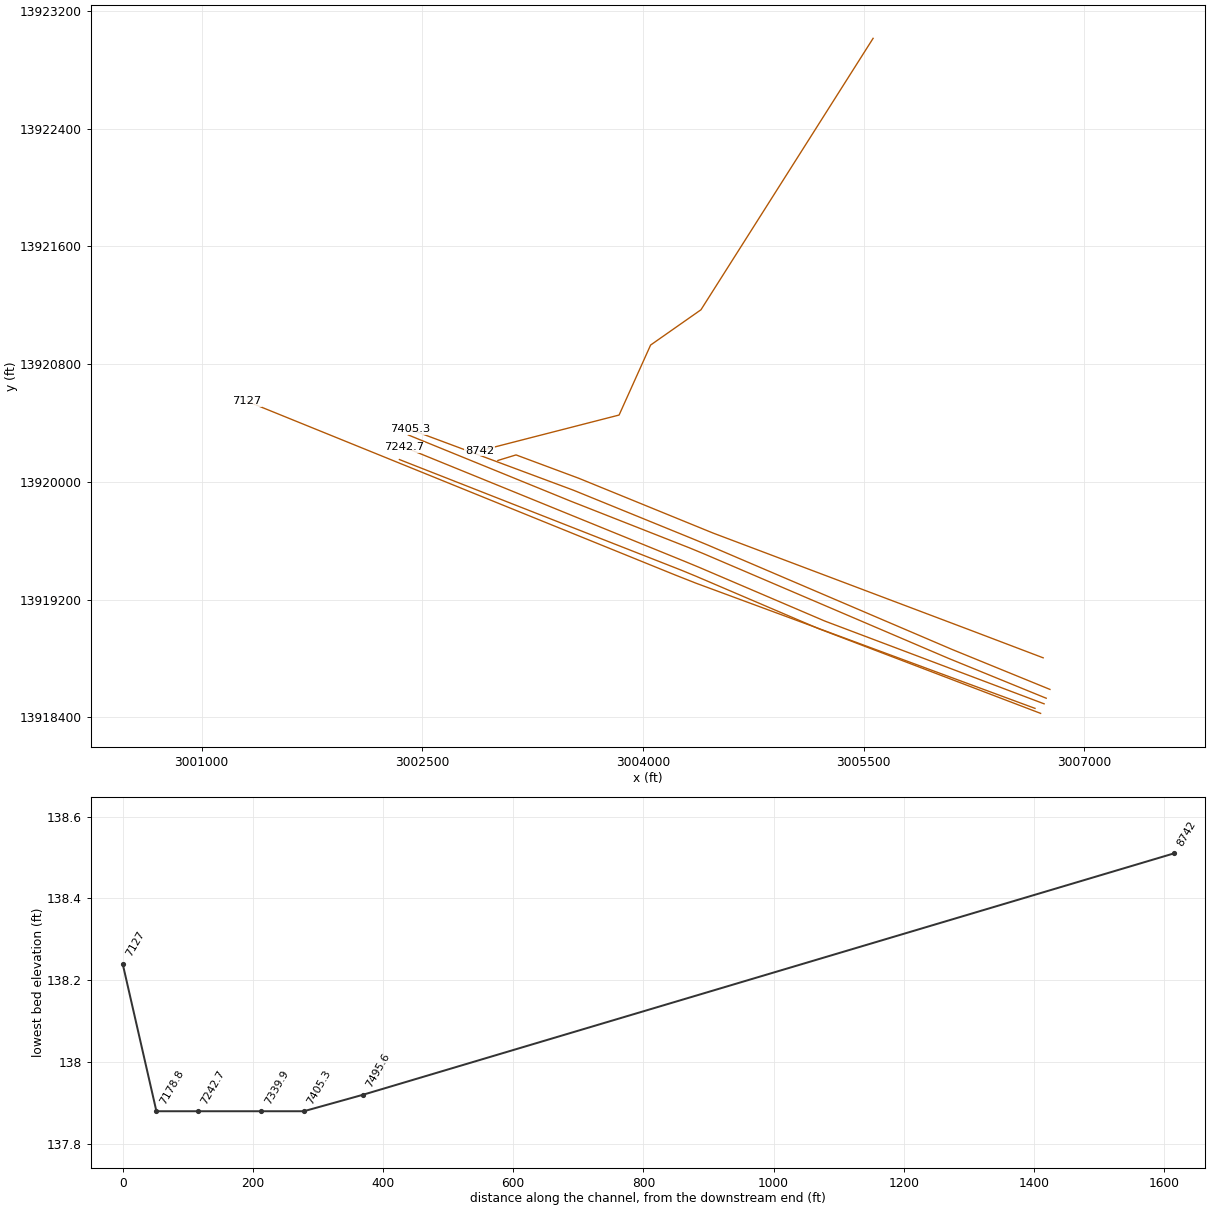
HEC-RAS study K159-00-00.prj: K159-00-00

--- K159-00-00.g01 (geometry) --- (continued)

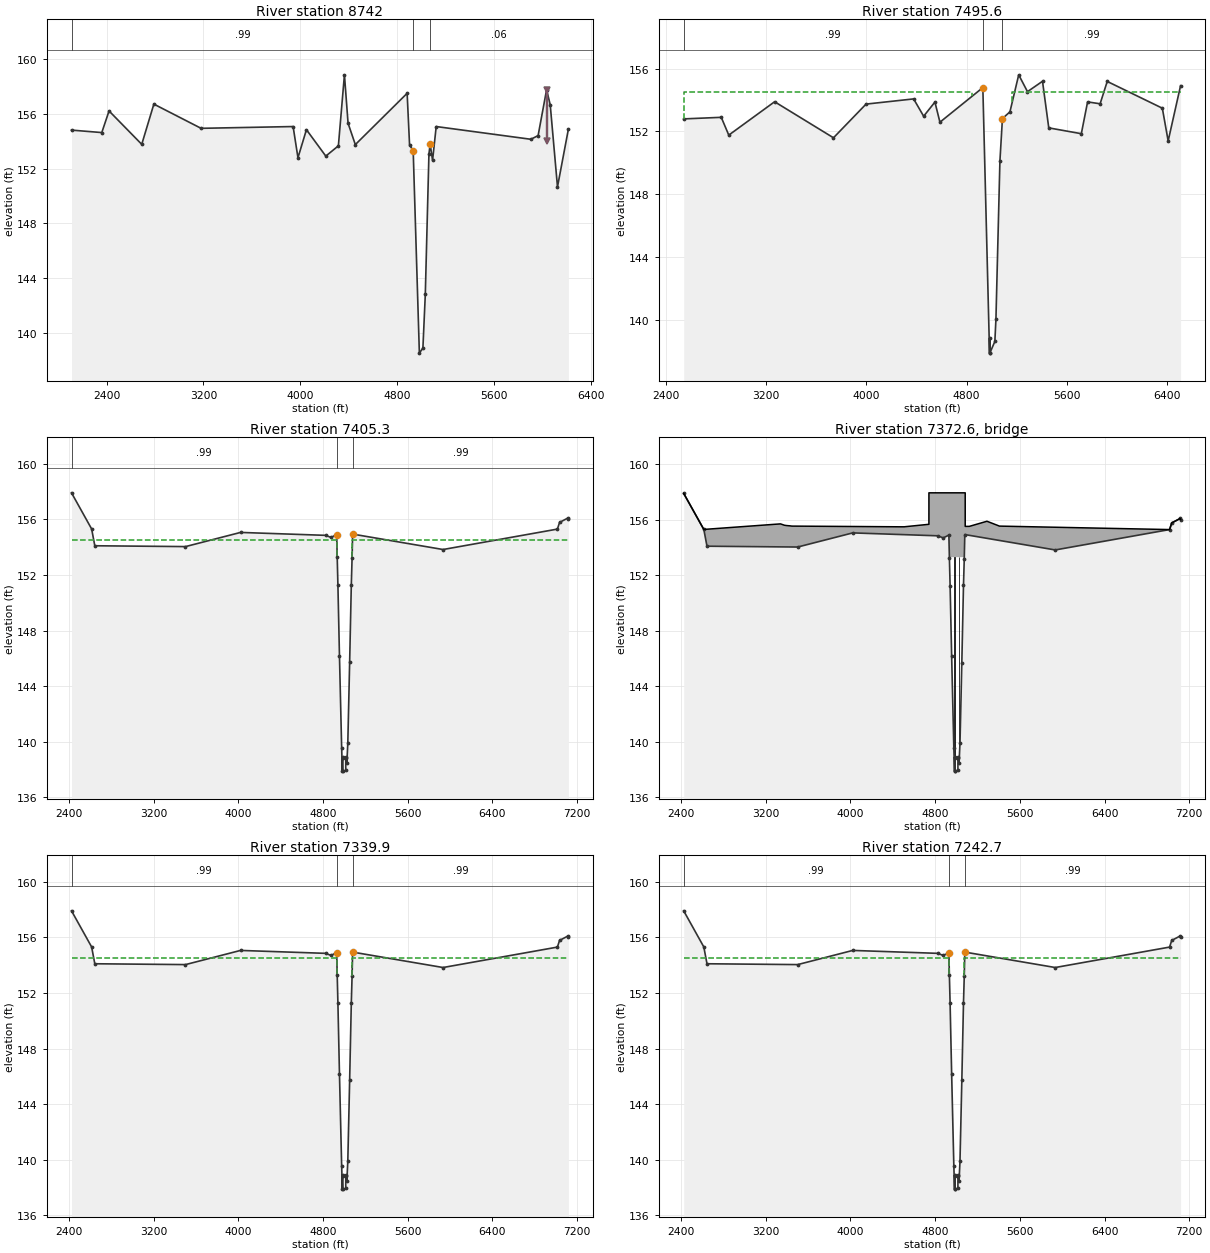
Type RM Length L Ch R = 1 ,8742    ,1369.1,1246.4,1140.5
BEGIN DESCRIPTION:
K159-00-00-XS interpolated 1
The levee set on the right overbank at station 6034 is used to isolate the far ROB ditch and is not intended as a certified flood-control levee.
END DESCRIPTION:
XS GIS Cut Line= 5
      3005563.53     13923013.39      3004393.81     13921169.26
      3004051.58     13920929.56       3003837.4     13920454.02
      3002888.11      13920210.4
#Sta/Elev= 30
  2110.8  154.81  2360.8  154.63  2420.8  156.21  2690.8  153.77  2790.8  156.71
  3180.8  154.94  3940.8  155.07  3980.8  152.79  4050.8  154.84  4210.8  152.91
  4314.6  153.66  4364.6  158.85  4394.6  155.31  4454.6  153.75  4882.4   157.5
  4902.4  153.73  4932.4   153.3  4983.4  138.51  5012.6  138.88  5032.4   142.8
  5062.4  153.06  5072.4  153.78  5092.4   152.6  5122.4  155.07    5904  154.14
    5964  154.41    6034  157.76    6064  156.66    6124  150.66    6214  154.88
#Mann= 3 ,-1 , 0
  2110.8     .99       0  4932.4     .04       0  5072.4     .06       0
Levee=0,,,-1,6034,154,,
Bank Sta=4932.4,5072.4
XS Rating Curve= 0
Exp/Cntr=.3,.1

Type RM Length L Ch R = 1 ,7495.6  ,89.8,90.3,90.9
BEGIN DESCRIPTION:
US 290 northbound - XS4
END DESCRIPTION:
XS GIS Cut Line= 6
      3006719.26     13918804.53      3006236.83      13918987.8
      3004474.66     13919652.69      3003564.83     13920023.89
      3003137.05     13920183.13      3003013.61     13920145.38
#Sta/Elev= 30
  2540.7   152.8  2840.7   152.9  2900.7  151.77  3266.8  153.89  3736.8   151.6
  3996.8  153.74  4376.8  154.07  4456.8  152.97  4546.8  153.87  4586.8  152.59
 4929.51  154.79 4983.03  137.92 4984.24  138.86 4985.26  137.92 5025.41  138.66
 5033.97  140.06  5065.9  150.13  5085.9  152.82  5145.9  153.25  5215.9   155.6
  5285.9  154.53  5405.9  155.19  5455.9  152.23  5715.9  151.86  5765.9  153.88
  5865.9  153.76  5922.8  155.18  6362.8  153.48  6409.3   151.4  6508.4  154.91
#Mann= 3 ,-1 , 0
  2540.7     .99       0 4929.51     .03       0  5085.9     .99       0
#XS Ineff= 2 , 0
       0 4844.07   154.5    5165       0   154.5
Permanent Ineff=
       F       F
Bank Sta=4929.51,5085.9
XS Rating Curve= 0
Exp/Cntr=.5,.3

Type RM Length L Ch R = 1 ,7405.3  ,65.3,65.4,66
BEGIN DESCRIPTION:
US 290 northbound - XS3
The levee set on the right overbank at station 6000 is used to isolate the far ROB ditch and is not intended as a certified flood-control levee.
END DESCRIPTION:
XS GIS Cut Line= 6
       3006765.2       13918590.      3006101.89     13918860.78
      3004437.78     13919571.82      3004340.12     13919612.17
      3003527.94     13919943.02      3002418.62     13920355.98
#Sta/Elev= 30
  2425.1  157.91  2615.1  155.31  2645.1   154.1  3501.5  154.04  4021.5  155.06
    4824  154.85    4876   154.7  4929.3   154.9 4934.27  153.26  4940.9  151.26
  4955.6  146.15  4976.2  139.56    4983  137.88  4984.3  138.89  4985.3  138.85
  4985.4  137.88  5014.8  137.93  5014.9  138.84  5017.6   138.9  5025.7  138.49
  5034.3  139.89  5051.7  145.71  5067.4  151.28 5074.67  153.21  5079.9  154.94
  5933.8  153.83  7013.8   155.3  7033.8  155.78  7113.8   156.1  7117.4  156.02
#Mann= 3 ,-1 , 0
  2425.1     .99       0  4929.3     .03       0  5079.9     .99       0
#XS Ineff= 2 , 0
       0 4934.07   154.5    5075       0   154.5
Permanent Ineff=
       F       F
Bank Sta=4929.3,5079.9
XS Rating Curve= 0
Exp/Cntr=.5,.3

Type RM Length L Ch R = 3 ,7372.6  ,,,
BEGIN DESCRIPTION:
US290 NORTHBOUND
Structure ID: K159-00-00-S06
END DESCRIPTION:
Bridge Culvert--1,0,-1,-1, 0
Deck Dist Width WeirC Skew NumUp NumDn MinLoCord MaxHiCord MaxSubmerge Is_Ogee
10,46,2.6,0, 25, 25, , , .95, 0, ,,,
  2425.1  2615.1  3338.3  3347.3  3377.3  3378.3  3397.3  3427.3  3447.3  4474.6
  4477.3  4487.3  4507.3 4740.79  4740.9  5083.6 5083.71  5120.5    5122  5288.9
  5407.3  7013.8  7033.8  7113.8  7117.4
  157.91  155.31  155.71  155.69  155.61  155.61  155.59  155.57  155.55   155.5
   155.5   155.5   155.5  155.68  157.95  157.95  155.53  155.53  155.53   155.9
  155.55   155.3  155.78   156.1  156.02
                                                                                
                                  153.31  153.31  154.92  154.87  154.87
                                        
  2425.1  2615.1  3338.3  3347.3  3377.3  3378.3  3397.3  3427.3  3447.3  4474.6
  4477.3  4487.3  4507.3 4740.79  4740.9  5083.6 5083.71  5120.5    5122  5288.9
  5407.3  7013.8  7033.8  7113.8  7117.4
  157.91  155.31  155.71  155.69  155.61  155.61  155.59  155.57  155.55   155.5
   155.5   155.5   155.5  155.68  157.95  157.95  155.53  155.53  155.53   155.9
  155.55   155.3  155.78   156.1  156.02
                                                                                
                                  153.31  153.31  154.92  154.87  154.87
                                        
Pier Skew, UpSta & Num, DnSta & Num=  ,4983, 2 ,4983, 2 , 0 , 0 , 0 ,,
       3       3
  137.24  154.31
       3       3
  137.38  154.45
Pier Skew, UpSta & Num, DnSta & Num=  ,5025.7, 2 ,5025.7, 2 , 0 , 0 , 0 ,,
       3       3
  137.56   154.3
       3       3
   137.7  154.44
BR Coef= 1 , 1 , 1 ,1.05, 0 ,,,.8,0,1.2,0,
WSPro=,,,, 1 ,,,, 0 ,,,, 0 ,,,,-1 ,-1 ,-1 , 0 , 0 , 0 , 0 , 0
BC Design=,, 0 ,, 0 ,,,,,,
BC HTab HWMax=157.91

Type RM Length L Ch R = 1 ,7339.9  ,97.2,97.2,97.1
BEGIN DESCRIPTION:
US 290 northbound - XS3
The levee set on the right overbank at station 6000 is used to isolate the far ROB ditch and is not intended as a certified flood-control levee.
END DESCRIPTION:
XS GIS Cut Line= 6
      3006739.86       13918530.       3006075.4     13918801.08
      3004413.54     13919511.16      3004315.87     13919551.51
      3003507.69     13919869.28      3002405.36     13920318.42
#Sta/Elev= 30
  2425.1  157.91  2615.1  155.31  2645.1   154.1  3501.5  154.04  4021.5  155.06
    4824  154.85    4876   154.7  4929.3   154.9 4934.27  153.26  4940.9  151.26
  4955.6  146.15  4976.2  139.56    4983  137.88  4984.3  138.89  4985.3  138.85
  4985.4  137.88  5014.8  137.93  5014.9  138.84  5017.6   138.9  5025.7  138.49
  5034.3  139.89  5051.7  145.71  5067.4  151.28 5074.67  153.21  5079.9  154.94
  5933.8  153.83  7013.8   155.3  7033.8  155.78  7113.8   156.1  7117.4  156.02
#Mann= 3 ,-1 , 0
  2425.1     .99       0  4929.3     .03       0  5079.9     .99       0
#XS Ineff= 2 , 0
       0 4934.03   154.5 5074.78       0   154.5
Permanent Ineff=
       F       F
Bank Sta=4929.3,5079.9
XS Rating Curve= 0
Exp/Cntr=.5,.3

Type RM Length L Ch R = 1 ,7242.7  ,63.5,63.9,64.4
BEGIN DESCRIPTION:
US 290 southbound - XS3
END DESCRIPTION:
XS GIS Cut Line= 5
      3006725.61       13918492.      3005235.93     13919054.11
      3004380.64     13919419.56      3004282.99      13919459.9
      3002377.75     13920235.56
#Sta/Elev= 30
  2425.1  157.91  2615.1  155.31  2645.1   154.1  3501.5  154.04  4021.5  155.06
    4824  154.85    4876   154.7  4929.3   154.9 4934.27  153.26  4940.9  151.26
  4955.6  146.15  4976.2  139.56    4983  137.88  4984.3  138.89  4985.3  138.85
  4985.4  137.88  5014.8  137.93  5014.9  138.84  5017.6   138.9  5025.7  138.49
  5034.3  139.89  5051.7  145.71  5067.4  151.28 5074.67  153.21  5079.9  154.94
  5933.8  153.83  7013.8   155.3  7033.8  155.78  7113.8   156.1  7117.4  156.02
#Mann= 3 ,-1 , 0
  2425.1     .99       0  4929.3     .03       0  5079.9     .99       0
#XS Ineff= 2 , 0
       0 4934.03   154.5 5074.78       0   154.5
Permanent Ineff=
       F       F
Bank Sta=4929.3,5079.9
XS Rating Curve= 0
Exp/Cntr=.5,.3

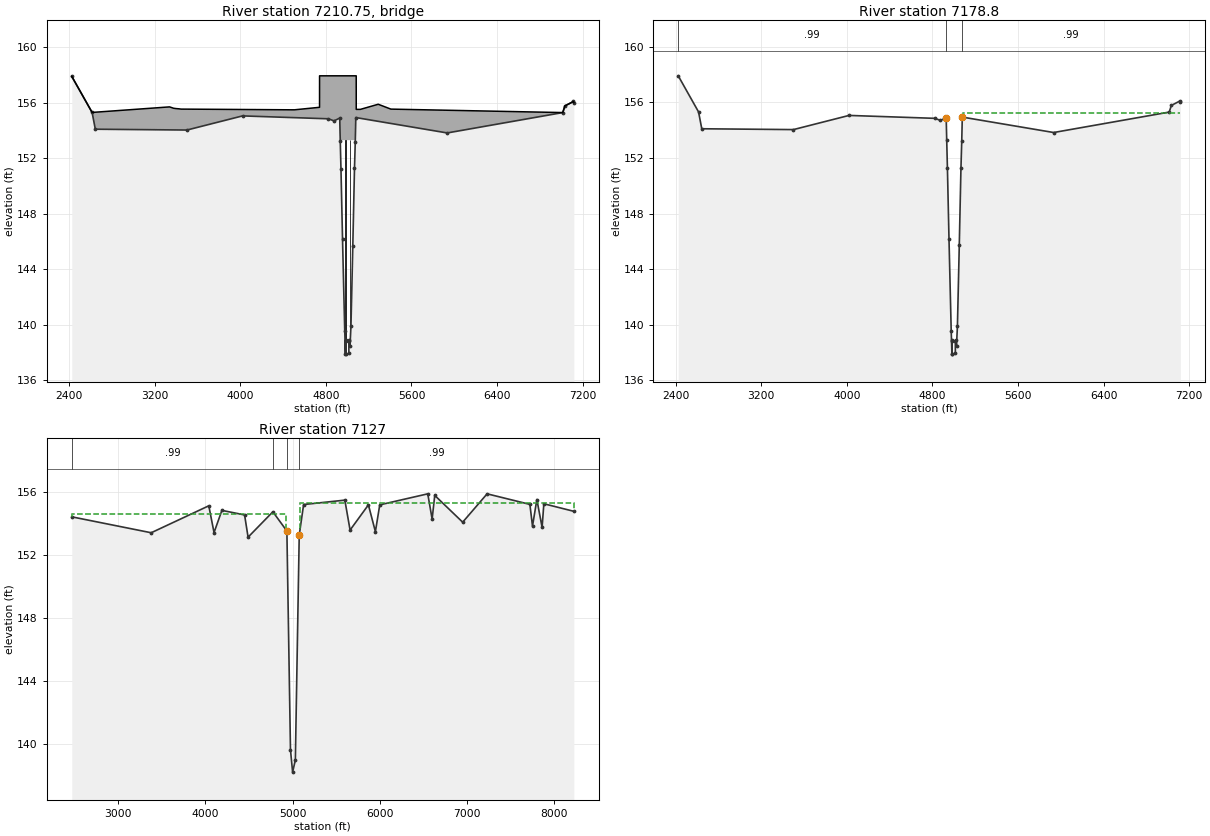
Type RM Length L Ch R = 3 ,7210.75 ,,,
BEGIN DESCRIPTION:
US290 SOUTHBOUND
Structure ID: K159-00-00-S06
END DESCRIPTION:
Bridge Culvert--1,0,-1,-1, 0
Deck Dist Width WeirC Skew NumUp NumDn MinLoCord MaxHiCord MaxSubmerge Is_Ogee
10,46,2.6,0, 25, 25, , , .95, 0, ,,,
  2425.1  2615.1  3338.3  3347.3  3377.3  3378.3  3397.3  3427.3  3447.3  4474.6
  4477.3  4487.3  4507.3 4740.79  4740.9  5083.6 5083.71  5120.5    5122  5288.9
  5407.3  7013.8  7033.8  7113.8  7117.4
  157.91  155.31  155.71  155.69  155.61  155.61  155.59  155.57  155.55   155.5
   155.5   155.5   155.5  155.68  157.95  157.95  155.53  155.53  155.53   155.9
  155.55   155.3  155.78   156.1  156.02
                                                                                
                                  153.31  153.31  154.92  154.87  154.87
                                        
  2425.1  2615.1  3338.3  3347.3  3377.3  3378.3  3397.3  3427.3  3447.3  4474.6
  4477.3  4487.3  4507.3 4740.79  4740.9  5083.6 5083.71  5120.5    5122  5288.9
  5407.3  7013.8  7033.8  7113.8  7117.4
  157.91  155.31  155.71  155.69  155.61  155.61  155.59  155.57  155.55   155.5
   155.5   155.5   155.5  155.68  157.95  157.95  155.53  155.53  155.53   155.9
  155.55   155.3  155.78   156.1  156.02
                                                                                
                                  153.31  153.31  154.92  154.87  154.87
                                        
Pier Skew, UpSta & Num, DnSta & Num=  ,4983, 2 ,4983, 2 , 0 , 0 , 0 ,,
       3       3
  137.24  154.31
       3       3
  137.38  154.45
Pier Skew, UpSta & Num, DnSta & Num=  ,5025.7, 2 ,5025.7, 2 , 0 , 0 , 0 ,,
       3       3
  137.56   154.3
       3       3
   137.7  154.44
BR Coef= 1 , 1 , 1 ,1.05, 0 ,,,.8,0,1.2,0,
WSPro=,,,, 1 ,,,, 0 ,,,, 0 ,,,,-1 ,-1 ,-1 , 0 , 0 , 0 , 0 , 0
BC Design=,, 0 ,, 0 ,,,,,,
BC HTab HWMax=157.91

Type RM Length L Ch R = 1 ,7178.8  ,43.6,51.8,45.6
BEGIN DESCRIPTION:
US 290 southbound - XS2
END DESCRIPTION:
XS GIS Cut Line= 5
      3006701.84      13918427.1       3005195.9     13919001.66
       3004360.5     13919358.61      3004262.83     13919398.96
       3002344.6     13920151.59
#Sta/Elev= 30
  2425.1  157.91  2615.1  155.31  2645.1   154.1  3501.5  154.04  4021.5  155.06
    4824  154.85    4876   154.7  4929.3   154.9 4934.27  153.26  4940.9  151.26
  4955.6  146.15  4976.2  139.56    4983  137.88  4984.3  138.89  4985.3  138.85
  4985.4  137.88  5014.8  137.93  5014.9  138.84  5017.6   138.9  5025.7  138.49
  5034.3  139.89  5051.7  145.71  5067.4  151.28 5074.67  153.21  5079.9  154.94
  5933.8  153.83  7013.8   155.3  7033.8  155.78  7113.8   156.1  7117.4  156.02
#Mann= 3 ,-1 , 0
  2425.1     .99       0  4929.3     .03       0  5079.9     .99       0
#XS Ineff= 2 , 0
       0  4925.6   154.6  5087.1       0   155.2
Permanent Ineff=
       F       F
Bank Sta=4929.3,5079.9
XS Rating Curve= 0
Exp/Cntr=.5,.3

Type RM Length L Ch R = 1 ,7127    ,37,38,41.7
BEGIN DESCRIPTION:
Southern Pacific RR - XS3
END DESCRIPTION:
XS GIS Cut Line= 4
      3006663.69     13918461.16      3004361.63     13919310.95
      3004219.67     13919366.89      3001306.51      13920548.3
#Sta/Elev= 30
    2471  154.44    3381  153.43    4041  155.14    4101  153.44    4191  154.85
    4451  154.56    4491  153.15  4775.1  154.76  4935.6  153.54  4976.8  139.66
  5001.2  138.24  5032.6     139  5077.1  153.28  5127.3  155.22  5599.7   155.5
  5659.7   153.6  5869.7   155.2  5949.7   153.5  5999.7   155.2  6549.7   155.9
  6599.7   154.3  6629.7   155.8  6949.7   154.1  7229.7   155.9  7719.7  155.23
  7749.7  153.85  7799.7  155.54  7859.7  153.77  7879.7  155.27  8223.4  154.79
#Mann= 4 ,-1 , 0
    2471     .99       0  4775.1     .06       0  4935.6     .03       0
  5077.1     .99       0
#XS Ineff= 2 , 0
       0  4925.6   154.6  5087.1       0   155.3
Permanent Ineff=
       F       F
Bank Sta=4935.6,5077.1
XS Rating Curve= 0
Exp/Cntr=.5,.3