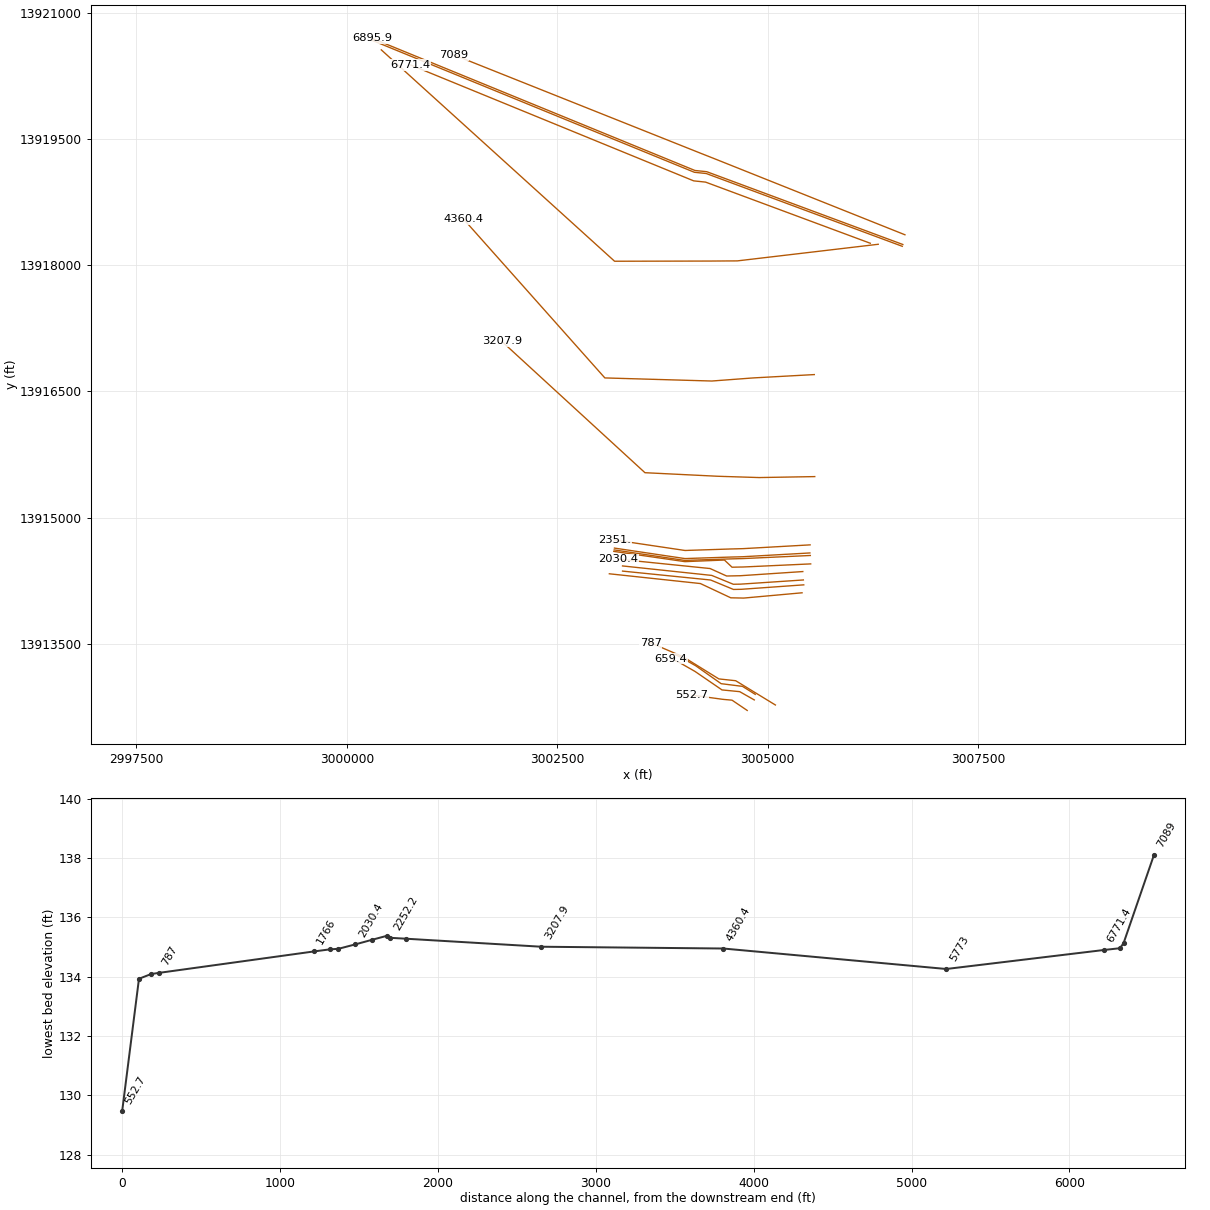
HEC-RAS study K159-00-00.prj: K159-00-00

--- K159-00-00.g01 (geometry) --- (continued)

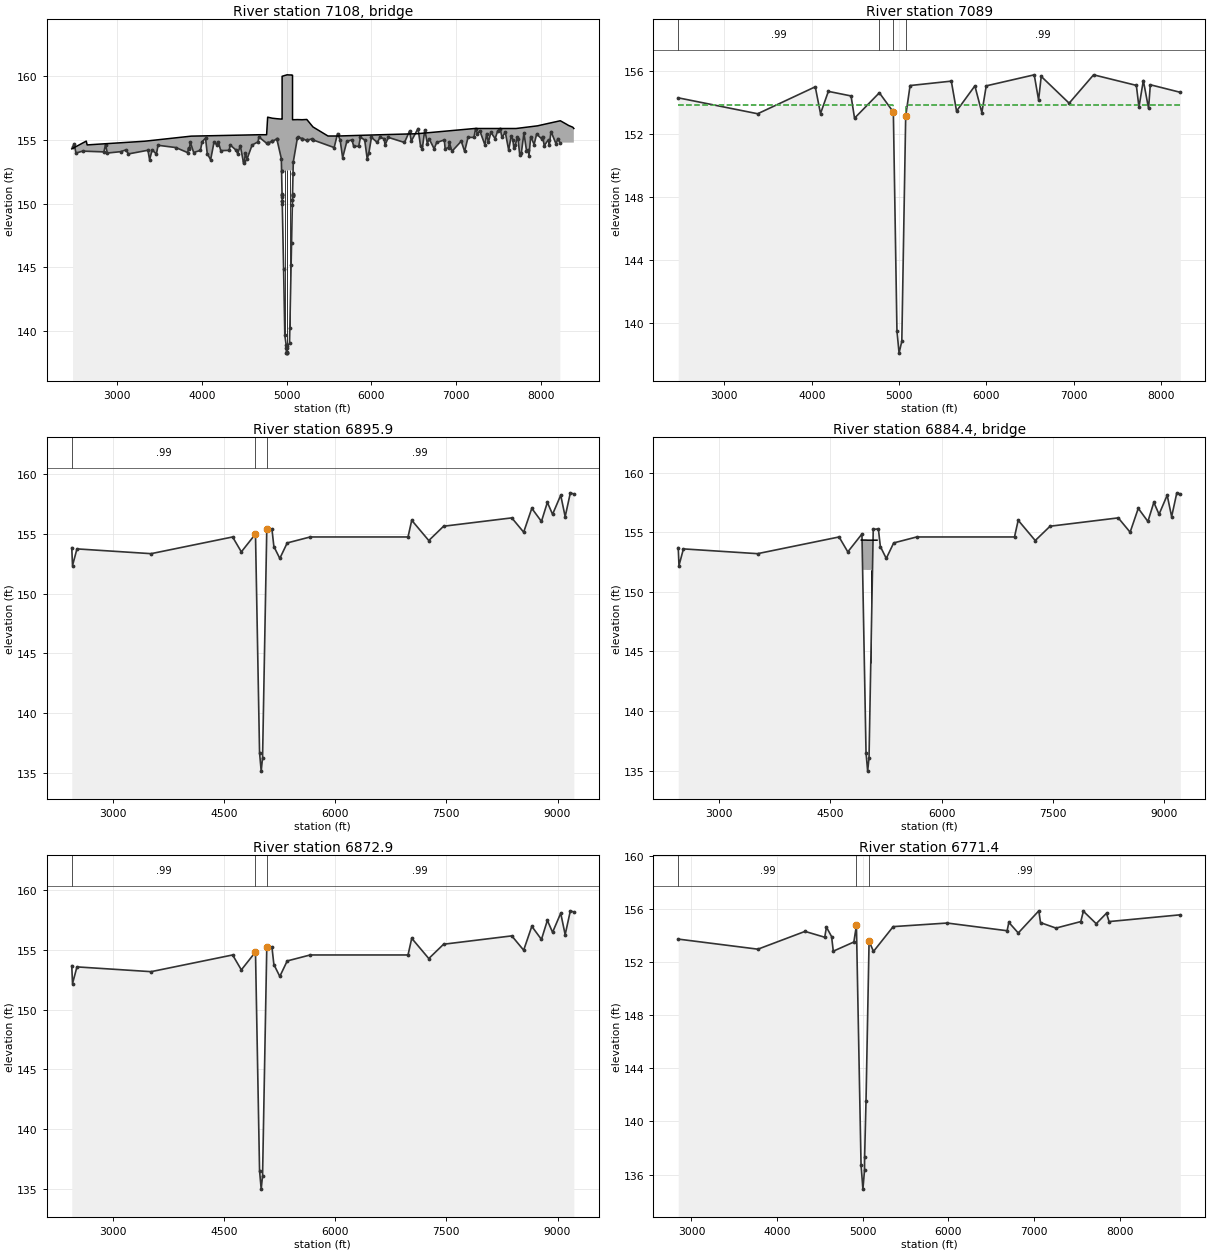
Type RM Length L Ch R = 3 ,7108    ,,,
BEGIN DESCRIPTION:
SOUTHERN PACIFIC RAILROAD
Structure ID: K159-00-00-S04
END DESCRIPTION:
Bridge Culvert--1,0,-1,-1, 0
Deck Dist Width WeirC Skew NumUp NumDn MinLoCord MaxHiCord MaxSubmerge Is_Ogee
10,18,2.6,0, 76, 76, , , .95, 0, ,,,
    2462  2633.3  2643.3    3322    3872  4673.3    4762  4774.4  4775.1  4829.1
  4829.4  4882.3  4882.6  4935.6 4938.89 4938.98 4944.89    4945 4945.11  4945.6
  4946.7  4946.8  4947.4  4962.7  4976.8  4993.1  4994.7    4995  5001.2  5003.4
  5005.1  5005.3  5006.5  5007.3  5032.6  5036.5  5051.3  5056.5  5065.3  5066.5
  5066.6  5067.7 5067.89    5068 5068.11  5073.8 5073.91  5077.1  5125.1  5127.3
  5179.8  5181.5  5233.9  5236.7  5294.7  5309.8  5486.5  5488.9  5519.8  5539.8
  5609.8  6056.5  6539.8  7216.5  7606.5  7706.5  7959.8  7966.5  7986.5  8046.5
  8066.5  8229.2  8306.5  8326.5  8376.5  8388.9
   154.3  154.91  154.61   154.9   155.3  155.41  155.41  156.79  156.79  156.71
  156.71  156.67  156.67  156.64  156.64  156.64  156.64  160.01  160.01  160.01
  160.01  160.01  160.01  160.04  160.07   160.1   160.1   160.1  160.12  160.12
  160.12  160.12  160.12  160.12  160.11  160.11  160.11  160.11  160.09  160.09
  160.09  160.09  160.09  160.09  156.59  156.59  156.59  156.59   156.6   156.6
  156.59  156.59  156.61  156.61  156.14  156.02  155.31  155.31  155.31  155.31
  155.31   155.4  155.49   155.9   155.9   155.9  156.11  156.12  156.15  156.24
  156.27  156.51  156.22  156.14     156   155.9
                                                                                
                                  152.56  152.64  152.64  152.64  152.64  152.64
  152.64  152.64  152.64  152.64   152.6   152.6   152.6   152.6  152.62  152.62
  152.62  152.62  152.62  152.62  152.61  152.61  152.61  152.61  152.59  152.59
  152.59  152.59  152.59  152.59  152.59  152.59  152.38
                                                                                
                                                                                
                                                
    2462  2633.3  2643.3    3322    3872  4673.3    4762  4774.4  4775.1  4829.1
  4829.4  4882.3  4882.6  4935.6 4938.89 4938.98 4944.89    4945 4945.11  4945.6
  4946.7  4946.8  4947.4  4962.7  4976.8  4993.1  4994.7    4995  5001.2  5003.4
  5005.1  5005.3  5006.5  5007.3  5032.6  5036.5  5051.3  5056.5  5065.3  5066.5
  5066.6  5067.7 5067.89    5068 5068.11  5073.8 5073.91  5077.1  5125.1  5127.3
  5179.8  5181.5  5233.9  5236.7  5294.7  5309.8  5486.5  5488.9  5519.8  5539.8
  5609.8  6056.5  6539.8  7216.5  7606.5  7706.5  7959.8  7966.5  7986.5  8046.5
  8066.5  8229.2  8306.5  8326.5  8376.5  8388.9
   154.3  154.91  154.61   154.9   155.3  155.41  155.41  156.79  156.79  156.71
  156.71  156.67  156.67  156.64  156.64  156.64  156.64  160.01  160.01  160.01
  160.01  160.01  160.01  160.04  160.07   160.1   160.1   160.1  160.12  160.12
  160.12  160.12  160.12  160.12  160.11  160.11  160.11  160.11  160.09  160.09
  160.09  160.09  160.09  160.09  156.59  156.59  156.59  156.59   156.6   156.6
  156.59  156.59  156.61  156.61  156.14  156.02  155.31  155.31  155.31  155.31
  155.31   155.4  155.49   155.9   155.9   155.9  156.11  156.12  156.15  156.24
  156.27  156.51  156.22  156.14     156   155.9
                                                                                
                                  152.56  152.64  152.64  152.64  152.64  152.64
  152.64  152.64  152.64  152.64   152.6   152.6   152.6   152.6  152.62  152.62
  152.62  152.62  152.62  152.62  152.61  152.61  152.61  152.61  152.59  152.59
  152.59  152.59  152.59  152.59  152.59  152.59  152.38
                                                                                
                                                                                
                                                
Pier Skew, UpSta & Num, DnSta & Num=  ,4976.8, 2 ,4976.8, 2 , 0 , 0 , 0 ,,
       2       2
  138.62  153.57
       2       2
  138.63  153.58
Pier Skew, UpSta & Num, DnSta & Num=  ,5006.5, 2 ,5006.5, 2 , 0 , 0 , 0 ,,
       2       2
  137.75  153.62
       2       2
  137.76  153.63
Pier Skew, UpSta & Num, DnSta & Num=  ,5036.5, 2 ,5036.5, 2 , 0 , 0 , 0 ,,
       2       2
  138.91  153.61
       2       2
  138.92  153.62
BR Coef= 1 , 1 , 1 ,1.05, 0 ,,,.8,0,1.2,0,
WSPro=,,,, 1 ,,,, 0 ,,,, 0 ,,,,-1 ,-1 ,-1 , 0 , 0 , 0 , 0 , 0
BR U #Sta/Elev= 166
    2471  154.44    2491   154.7    2511  153.97    2591  154.12    2841  154.06
    2861  154.63    2881  153.97    3041  154.08    3101  154.22    3131   153.9
    3361  154.19    3381  153.43    3411  154.22    3461  153.89    3481  154.58
    3691   154.4    3831     154    3841  154.39    3851  154.27    3861  154.82
    3901  154.01    3981  154.18    4001  154.86    4041  155.14    4061  153.93
    4101  153.44    4141  154.81    4171  154.64    4191  154.85    4221  154.16
    4321  154.18    4331  154.61    4401   154.2    4421   153.9    4451  154.56
    4491  153.15    4501  153.32    4511  153.97    4531   153.5    4591   154.6
    4661  154.85    4671  155.23    4762  154.74  4774.4  154.76  4775.1  154.76
  4829.1  154.89  4829.4  154.89  4882.3  155.08  4882.6  155.08  4935.6  153.54
  4938.8  152.55  4938.9  152.52 4944.89  150.75    4945  150.71 4945.11  150.68
  4945.6  150.53  4946.7   150.2  4946.8  150.17  4947.4  149.99  4962.7  144.88
  4976.8  139.66  4993.1  138.86  4994.7  138.65    4995  138.26  5001.2  138.24
  5003.4  138.27  5005.1  138.29  5005.3  138.63  5007.3  138.82  5032.6     139
  5036.5  140.21  5051.3  145.17  5056.5  146.93  5065.3  149.92  5066.5  150.26
  5066.6  150.29  5067.7   150.6 5067.89  150.66    5068  150.69 5068.11  150.72
  5073.8  152.345073.915  152.37  5077.1  153.28  5125.1  155.13  5127.3  155.22
  5179.8  155.11  5181.5  155.11  5233.9  154.96  5236.7  154.97  5294.7  155.08
  5309.7     155  5559.7   154.4  5599.7   155.5  5629.7     155  5659.7   153.6
  5709.7   154.9  5769.7     155  5789.7   154.5  5849.7   154.5  5869.7   155.2
  5919.7     155  5949.7   153.5  5969.7     154  5999.7   155.2  6069.7   154.8
  6099.7   155.2  6149.7   155.1  6159.7   154.6  6199.7   155.2  6389.7   154.8
  6449.7   155.7  6469.7   154.9  6549.7   155.9  6579.7   154.5  6599.7   154.3
  6629.7   155.8  6659.7   154.7  6679.7   155.1  6739.7   154.3  6769.7   154.8
  6859.7     155  6869.7   154.3  6909.7   154.4  6919.7   154.8  6949.7   154.1
  7059.7   154.9  7099.7   154.1  7139.7   155.2  7209.7   155.2  7229.7   155.9
  7249.7   155.5  7279.7   155.7  7339.7   154.6  7359.7   155.5  7379.7   154.8
  7409.7   155.6  7459.7   155.1  7489.7   155.7  7519.7   155.9  7539.7   155.2
  7579.7   155.6  7619.7   154.2  7649.7   155.3  7669.7     155  7679.7   154.4
  7699.7   154.6  7719.7  155.23  7729.7  155.09  7749.7  153.85  7769.7     154
  7799.7  155.54  7829.7  154.17  7849.7  154.18  7859.7  153.77  7879.7  155.27
  7919.7  154.64  7949.7  155.46  8009.7  155.08  8019.7  155.27  8039.7  154.55
  8089.7  155.03  8099.7  154.64  8119.7  155.66  8179.7  154.67  8199.7  155.11
  8223.4  154.79
BR U #Mann= 4
    2471     .99  4775.1     .06  4935.6     .03  5077.1     .99
BC Design=,, 0 ,, 0 ,,,,,,
BC HTab HWMax=155.9

Type RM Length L Ch R = 1 ,7089    ,177.4,193.1,215.6
BEGIN DESCRIPTION:
Southern Pacific RR - XS2
END DESCRIPTION:
XS GIS Cut Line= 4
      3006630.78     13918359.89      3004346.58     13919272.05
      3004204.52     13919328.03      3001273.42      13920496.3
#Sta/Elev= 30
    2471  154.31    3381   153.3    4041  155.01    4101  153.31    4191  154.72
    4451  154.43    4491  153.02  4775.1  154.63  4935.6  153.41  4976.8  139.53
  5001.2  138.11  5032.6  138.87  5077.1  153.15  5127.3  155.09  5599.7  155.37
  5659.7  153.47  5869.7  155.07  5949.7  153.37  5999.7  155.07  6549.7  155.77
  6599.7  154.17  6629.7  155.67  6949.7  153.97  7229.7  155.77  7719.7   155.1
  7749.7  153.72  7799.7  155.41  7859.7  153.64  7879.7  155.14  8223.4  154.66
#Mann= 4 ,-1 , 0
    2471     .99       0  4775.1     .06       0  4935.6     .03       0
  5077.1     .99       0
#XS Ineff= 2 , 0
       0 4928.93  153.87 5083.77       0  153.87
Permanent Ineff=
       F       F
Bank Sta=4935.6,5077.1
XS Rating Curve= 0
Exp/Cntr=.5,.3

Type RM Length L Ch R = 1 ,6895.9  ,22.5,23,22.8
BEGIN DESCRIPTION:
PL1_K159-00-00-S03 - XS3
The 0.2% floodplain spills towards the K152-00-00 (Cypress Creek Trib 37.1) watershed on the LOB
END DESCRIPTION:
XS GIS Cut Line= 4
      3006606.09      13918244.3      3004276.69     13919109.07
       3004135.5     13919123.82      3000297.66     13920695.19
#Sta/Elev= 30
  2446.1  153.86  2456.2  152.36  2516.1  153.76  3516.2  153.36  4616.1  154.76
 4733.96  153.51 4924.76  155.01 4979.66  136.69 5001.76  135.13 5020.26  136.26
 5077.06  155.39 5146.36  155.44  5172.9  153.96  5252.8  152.96  5352.8  154.26
  5662.8  154.76  6982.9  154.76  7032.8  156.16  7262.8  154.46  7462.8  155.66
  8382.8  156.36  8542.9  155.16  8652.8  157.16  8782.9  156.06  8862.8  157.66
  8932.9  156.66  9042.9  158.26  9102.9  156.46  9172.8  158.46    9220  158.36
#Mann= 3 ,-1 , 0
  2446.1     .99       0 4924.76     .05       0 5077.06     .99       0
#XS Ineff= 2 , 0
       0 4837.46  153.35 5087.06       0   152.8
Permanent Ineff=
       F       F
Bank Sta=4924.76,5077.06
XS Rating Curve= 0
Exp/Cntr=.5,.3

Type RM Length L Ch R = 3 ,6884.4  ,,,
BEGIN DESCRIPTION:
PL1_K159-00-00-S03
END DESCRIPTION:
Bridge Culvert--1,0,-1,-1, 0
Deck Dist Width WeirC Skew NumUp NumDn MinLoCord MaxHiCord MaxSubmerge Is_Ogee
10,3,2.6,0, 22, 22, , , .95, 0, ,,,
  4916.1 4924.76  4926.2 4928.36 4934.21  4934.3 4955.16 4977.56 4979.56 4979.66
 5001.76 5020.26 5020.46 5021.26 5034.96  5067.1 5067.21 5071.56  5072.8 5077.06
  5092.9 5127.96
  154.34  154.34  154.34  154.34  154.34  154.34  154.34  154.34  154.34  154.34
  154.33  154.33  154.33  154.33  154.33  154.33  154.33  154.33  154.33  154.33
  154.33  154.33
  154.34  154.34  154.34  153.72  151.88  151.85  151.84  151.84  151.84  151.84
  151.83  151.83  151.83  151.83  151.83  151.88  151.91  153.38  153.38  153.38
  153.38  153.38
  4916.1 4924.76  4926.2 4928.36 4934.21  4934.3 4955.16 4977.56 4979.56 4979.66
 5001.76 5020.26 5020.46 5021.26 5034.96  5067.1 5067.21 5071.56  5072.8 5077.06
  5092.9 5127.96
  154.34  154.34  154.34  154.34  154.34  154.34  154.34  154.34  154.34  154.34
  154.33  154.33  154.33  154.33  154.33  154.33  154.33  154.33  154.33  154.33
  154.33  154.33
  154.34  154.34  154.34  153.72  151.88  151.85  151.84  151.84  151.84  151.84
  151.83  151.83  151.83  151.83  151.83  151.88  151.91  153.38  153.38  153.38
  153.38  153.38
Pier Skew, UpSta & Num, DnSta & Num=  ,5043.7, 2 ,5043.7, 2 , 0 , 0 , 0 ,,
     1.5     1.5
  142.74  152.84
     1.5     1.5
  142.74  152.84
Pier Skew, UpSta & Num, DnSta & Num=  ,5046.4, 2 ,5046.4, 2 , 0 , 0 , 0 ,,
     1.5     1.5
  143.65  152.85
     1.5     1.5
  143.65  152.85
BR Coef= 1 , 1 , 1 ,1.05, 0 ,,,.8,-1,1.2,0,
WSPro=,,,, 1 ,,,, 0 ,,,, 0 ,,,,-1 ,-1 ,-1 , 0 , 0 , 0 , 0 , 0
BR U #Sta/Elev= 30
  2446.1   153.7  2456.2   152.2  2516.1   153.6  3516.2   153.2  4616.1   154.6
 4733.96  153.35 4924.76  154.85 4979.66  136.53 5001.76  134.97 5020.26   136.1
 5077.06  155.23 5146.36  155.28  5172.9   153.8  5252.8   152.8  5352.8   154.1
  5662.8   154.6  6982.9   154.6  7032.8     156  7262.8   154.3  7462.8   155.5
  8382.8   156.2  8542.9     155  8652.8     157  8782.9   155.9  8862.8   157.5
  8932.9   156.5  9042.9   158.1  9102.9   156.3  9172.8   158.3    9220   158.2
BR U #Mann= 3
  2446.1     .99 4924.76     .05 5077.06     .99
BR U Banks=4924.76,5077.06
BR D #Sta/Elev= 30
  2446.1   153.7  2456.2   152.2  2516.1   153.6  3516.2   153.2  4616.1   154.6
 4733.96  153.35 4924.76  154.85 4979.66  136.53 5001.76  134.97 5020.26   136.1
 5077.06  155.23 5146.36  155.28  5172.9   153.8  5252.8   152.8  5352.8   154.1
  5662.8   154.6  6982.9   154.6  7032.8     156  7262.8   154.3  7462.8   155.5
  8382.8   156.2  8542.9     155  8652.8     157  8782.9   155.9  8862.8   157.5
  8932.9   156.5  9042.9   158.1  9102.9   156.3  9172.8   158.3    9220   158.2
BR D #Mann= 3
  2446.1     .99 4924.76     .05 5077.06     .99
BR D Banks=4924.76,5077.06
BC Design=,, 0 ,, 0 ,,,,,,
BC HTab HWMax=158.46

Type RM Length L Ch R = 1 ,6872.9  ,101,101.5,99.8
BEGIN DESCRIPTION:
PL1_K159-00-00-S03 - XS2
The 0.2% floodplain spills towards the K152-00-00 (Cypress Creek Trib 37.1) watershed on the LOB
END DESCRIPTION:
XS GIS Cut Line= 4
      3006599.16     13918222.98      3004270.34     13919087.53
      3004129.07     13919102.29      3000290.57     13920673.93
#Sta/Elev= 30
  2446.1  153.69  2456.2  152.19  2516.1  153.59  3516.2  153.19  4616.1  154.59
 4733.96  153.34 4924.76  154.84 4979.66  136.52 5001.76  134.96 5020.26  136.09
 5077.06  155.22 5146.36  155.27  5172.9  153.79  5252.8  152.79  5352.8  154.09
  5662.8  154.59  6982.9  154.59  7032.8  155.99  7262.8  154.29  7462.8  155.49
  8382.8  156.19  8542.9  154.99  8652.8  156.99  8782.9  155.89  8862.8  157.49
  8932.9  156.49  9042.9  158.09  9102.9  156.29  9172.8  158.29    9220  158.19
#Mann= 3 ,-1 , 0
  2446.1     .99       0 4924.76     .05       0 5077.06     .99       0
#XS Ineff= 2 , 0
       0 4840.79  153.35 5083.73       0   152.8
Permanent Ineff=
       F       F
Bank Sta=4924.76,5077.06
XS Rating Curve= 0
Exp/Cntr=.5,.3

Type RM Length L Ch R = 1 ,6771.4  ,990.6,998.4,1014.3
BEGIN DESCRIPTION:
PL1_K159-00-00-S03 - XS1
END DESCRIPTION:
XS GIS Cut Line= 4
      3006219.12      13918259.1      3004262.49     13918985.48
      3004121.21     13919000.23      3000760.41     13920376.29
#Sta/Elev= 30
    2846  153.74    3776  152.98    4326  154.32    4556  153.88    4576  154.64
    4636  153.93    4656  152.83    4896  153.52 4925.98  154.77 4980.05  136.72
 5001.81   134.9 5020.54  136.33 5021.56  137.29 5037.89  141.52 5073.75  153.58
  5125.2  152.81  5355.2  154.68  5985.2  154.95  6685.2  154.37  6705.2     155
  6815.2   154.2  7055.2  155.87  7075.2  154.98  7255.2  154.57  7545.2  155.06
  7575.2  155.84  7725.2   154.9  7845.2  155.69  7875.2  155.06  8706.8  155.57
#Mann= 3 ,-1 , 0
    2846     .99       0 4925.98     .05       0 5073.75     .99       0
Bank Sta=4925.98,5073.75
XS Rating Curve= 0
Exp/Cntr=.3,.1

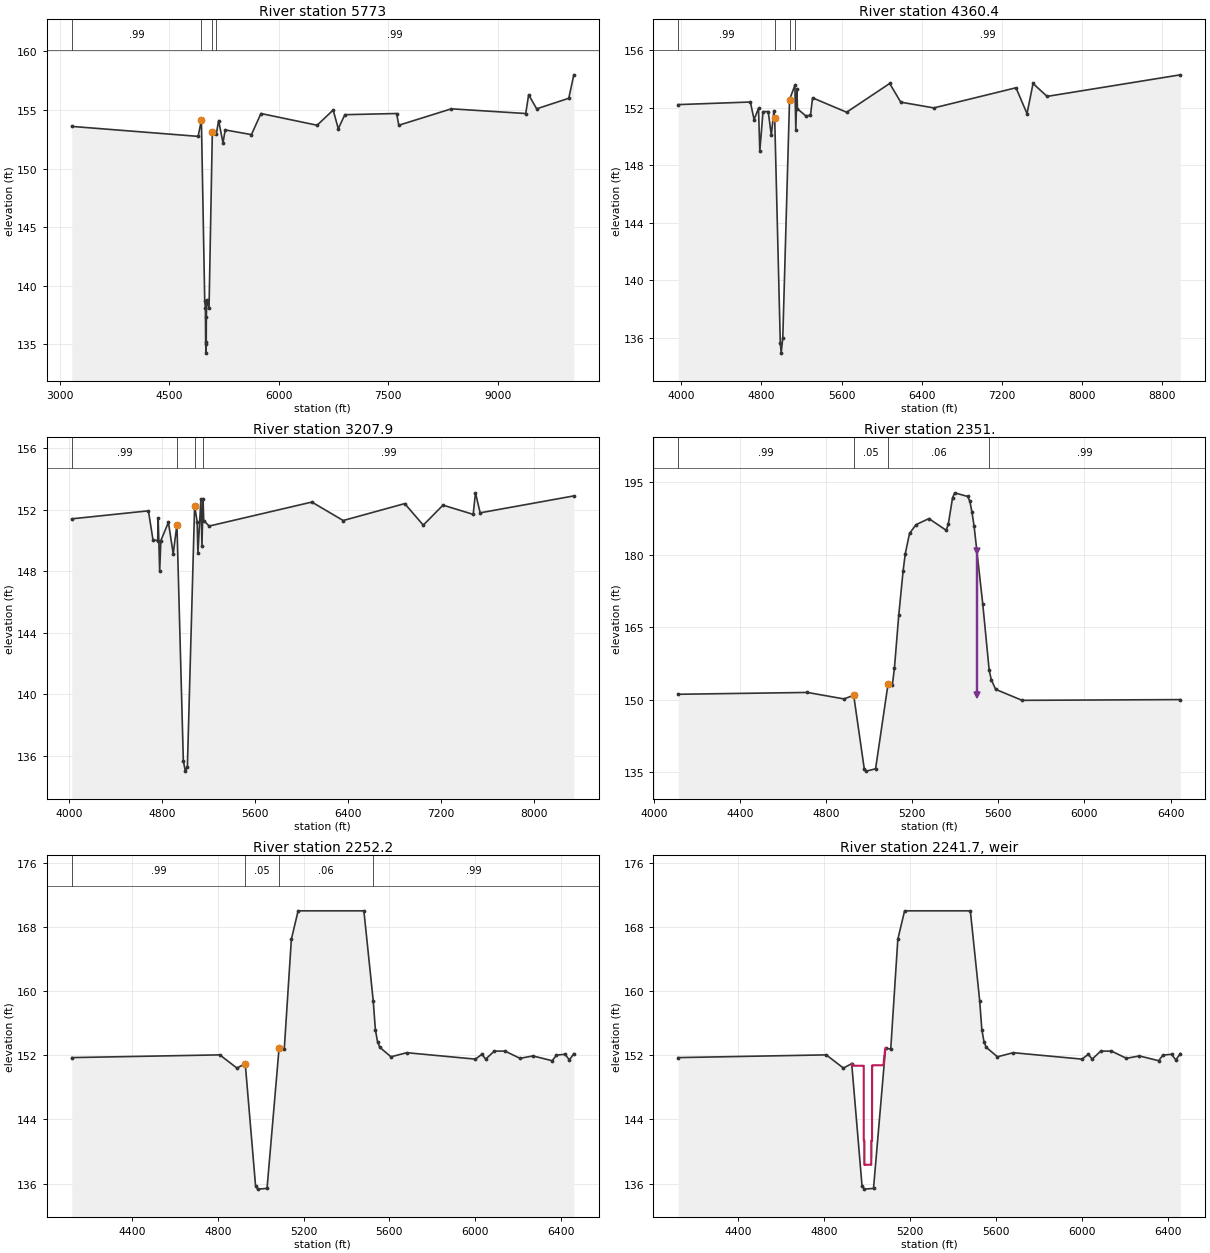
Type RM Length L Ch R = 1 ,5773    ,1408,1412.6,1418.4
BEGIN DESCRIPTION:
Cross Section K159-00-00-X05A
The 0.2% floodplain spills towards the K152-00-00 (Cypress Creek Trib 37.1) watershed on the LOB
END DESCRIPTION:
XS GIS Cut Line= 5
      3006313.65     13918246.96      3004639.24     13918049.55
      3004321.74     13918047.69       3003181.4     13918045.47
      3000410.01     13920556.45
#Sta/Elev= 30
  3160.7   153.6  4892.9  152.75    4938  154.12  4983.6  138.73  4993.1  138.14
  4996.3  135.17  5002.3  134.26  5004.1  135.03  5005.6  137.37  5012.4   138.8
  5042.8  138.13  5087.9  153.12  5141.8  152.93  5174.2   154.1  5234.2   152.2
  5264.2   153.3  5624.2   152.9  5754.2   154.7  6524.6   153.7  6744.6     155
  6814.6   153.4  6904.6   154.6  7614.6   154.7  7644.6   153.7  8364.6   155.1
  9384.6   154.7  9424.6   156.3  9534.6   155.1  9974.6     156 10044.3     158
#Mann= 4 ,-1 , 0
  3160.7     .99       0    4938     .05       0  5087.9     .06       0
  5141.8     .99       0
Bank Sta=4938,5087.9
XS Rating Curve= 0
Exp/Cntr=.3,.1

Type RM Length L Ch R = 1 ,4360.4  ,1160.1,1152.5,1142.6
BEGIN DESCRIPTION:
Cross Section K159-00-00-X5
The 0.2% floodplain spills towards the K152-00-00 (Cypress Creek Trib 37.1) watershed on the LOB
END DESCRIPTION:
XS GIS Cut Line= 5
        3005554.       13916699.      3004826.92     13916659.18
      3004336.11     13916622.43      3003065.93     13916659.18
  3001390.90250713918541.8608398
#Sta/Elev= 30
  3970.1  152.23  4690.1  152.41  4727.1  151.19  4771.4  151.97  4784.3  148.99
  4816.3  151.74  4868.2  151.75  4899.3   150.1  4924.5  151.79    4933  151.27
  4988.7  135.68  4997.7  134.95  5013.8  136.03  5081.1  152.58  5134.4  153.57
  5143.9  150.48  5154.5  153.34    5160  151.94  5242.1  151.45    5290  151.48
  5310.9   152.7  5650.9   151.7  6080.9   153.7  6190.9   152.4  6521.6     152
  7341.6   153.4  7451.6   151.6  7511.6   153.7  7651.6   152.8  8981.6   154.3
#Mann= 4 ,-1 , 0
  3970.1     .99       0    4933     .05       0  5081.1     .06       0
  5134.4     .99       0
Bank Sta=4933,5081.1
XS Rating Curve= 0
Exp/Cntr=.3,.1

Type RM Length L Ch R = 1 ,3207.9  ,853.4,856.9,864.1
BEGIN DESCRIPTION:
Cross Section K159-00-00-X4
The 0.2% floodplain spills towards the K152-00-00 (Cypress Creek Trib 37.1) watershed on the LOB
END DESCRIPTION:
XS GIS Cut Line= 5
       3005559.4       13915487.      3004899.09     13915475.57
        3004409.     13915490.89      3003542.26      13915533.3
        3001842.     13917093.21
#Sta/Elev= 30
  4020.1  151.41  4680.6  151.93  4719.7  150.05  4760.3  149.99  4764.7  151.46
  4777.5     148  4787.8     150  4852.8  151.18  4894.1  149.14  4926.3  151.04
  4981.4  135.68  4998.7  135.01  5016.3  135.31  5078.6  152.25  5100.5  151.23
  5107.1   149.2  5132.9  152.69  5141.8  149.65  5151.4  152.67    5157   151.3
  5203.9  150.94  6088.7   152.5  6358.7   151.3  6888.7   152.4  7048.7     151
  7218.7   152.3  7478.7   151.7  7498.7   153.1  7538.7   151.8  8346.1   152.9
#Mann= 4 ,-1 , 0
  4020.1     .99       0  4926.3     .05       0  5078.6     .06       0
  5151.4     .99       0
Bank Sta=4926.3,5078.6
XS Rating Curve= 0
Exp/Cntr=.3,.1

Type RM Length L Ch R = 1 ,2351.   ,96,98.8,96
BEGIN DESCRIPTION:
K159-00-00-S-0-2a_DAM - XS4
END DESCRIPTION:
XS GIS Cut Line= 5
       3005504.3     13914675.94      3004707.29     13914631.11
      3004550.94     13914626.89      3004018.54      13914609.3
      3003182.38      13914733.8
#Sta/Elev= 30
  4112.6  151.15  4712.6  151.53  4882.6  150.19 4927.73  150.95 4976.97  135.74
 4987.22  135.28 5029.55  135.77  5087.3  153.25  5107.3  153.01  5117.3  156.67
  5137.3  167.57  5157.3  176.58  5167.3  180.16  5187.3  184.38  5217.3  186.17
  5277.3  187.43  5357.3  185.02  5367.3  186.26  5387.3  191.77  5397.3  192.75
  5457.3     192  5467.3  191.04  5477.3  188.77  5487.3  185.83  5527.3  169.87
  5557.3  156.12  5567.3  154.13  5587.3  152.17    5710   149.9  6445.3  150.05
#Mann= 4 ,-1 , 0
  4112.6     .99       0 4927.73     .05       0  5087.3     .06       0
  5557.3     .99       0
Levee=0,,,-1,5500,151,,
Bank Sta=4927.73,5087.3
XS Rating Curve= 0
Exp/Cntr=.7,.5

Type RM Length L Ch R = 1 ,2252.2  ,21.9,21,20.8
BEGIN DESCRIPTION:
K159-00-00-S-0-2a_DAM - XS3
Elevations greater than 170.00 on the ROB were truncated.
Detention basin on ROB from K159-00 mouth to XS 2252.2
END DESCRIPTION:
XS GIS Cut Line= 5
      3005501.83     13914579.86      3004704.82     13914535.03
      3004548.47      13914530.8      3004016.08     13914513.21
      3003179.91     13914637.72
#Sta/Elev= 30
  4119.3   151.7  4809.3  152.04    4889   150.4  4927.9  150.94  4975.9  135.76
  4985.9  135.31  5029.5   135.4  5085.6  152.88  5109.8  152.76  5142.9  166.45
  5174.4  169.99  5480.9  169.99  5524.4   158.8  5534.4   155.2  5544.4   153.7
  5554.4     153  5607.1   151.8  5680.9  152.31  6000.9  151.51  6030.9  152.11
  6048.7  151.51  6088.7  152.51  6138.7  152.51  6208.7  151.61  6268.7  151.91
  6358.7  151.31  6378.7  152.01  6418.7  152.11  6438.7  151.41  6459.6   152.2
#Mann= 4 ,-1 , 0
  4119.3     .99       0  4927.9     .05       0  5085.6     .06       0
  5524.4     .99       0
#XS Ineff= 2 , 0
       0  4917.9   150.6  5119.8       0     151
Permanent Ineff=
       F       F
Bank Sta=4927.9,5085.6
XS Rating Curve= 0
Exp/Cntr=.7,.5

Type RM Length L Ch R = 5 ,2241.7  ,,,
BEGIN DESCRIPTION:
SHEET PILING DROP STRUCTURE 5000 FT D/S HWY 290 AND 330 FT U/S OF CULVERTS (2 BRIDGES) (S4 PER PHOTOS)
Structure ID: K159-00-00-S-0-2a
END DESCRIPTION:
IW Pilot Flow=0
#Inline Weir SE= 25
  4927.9  150.94    4928  150.92  4928.8  150.78  4932.9  150.69  4975.9   150.7
  4980.2   150.7  4984.1   150.7  4984.2  141.37  4985.9  141.38  4987.1  141.38
  4987.2  138.32  4993.4  138.34  5003.8  138.35  5013.6  138.35  5014.7  138.35
  5019.6  138.35  5019.7  139.87  5019.8  141.39  5022.8  141.36  5022.9  150.72
  5029.5  150.73  5075.4  150.76  5083.3  152.66  5084.4   152.7  5085.6  152.88
IW Dist,WD,Coef,Skew,MaxSub,Min_El,Is_Ogee,SpillHt,DesHd
10,1,3,0,.95,, 0 ,,,0,0,

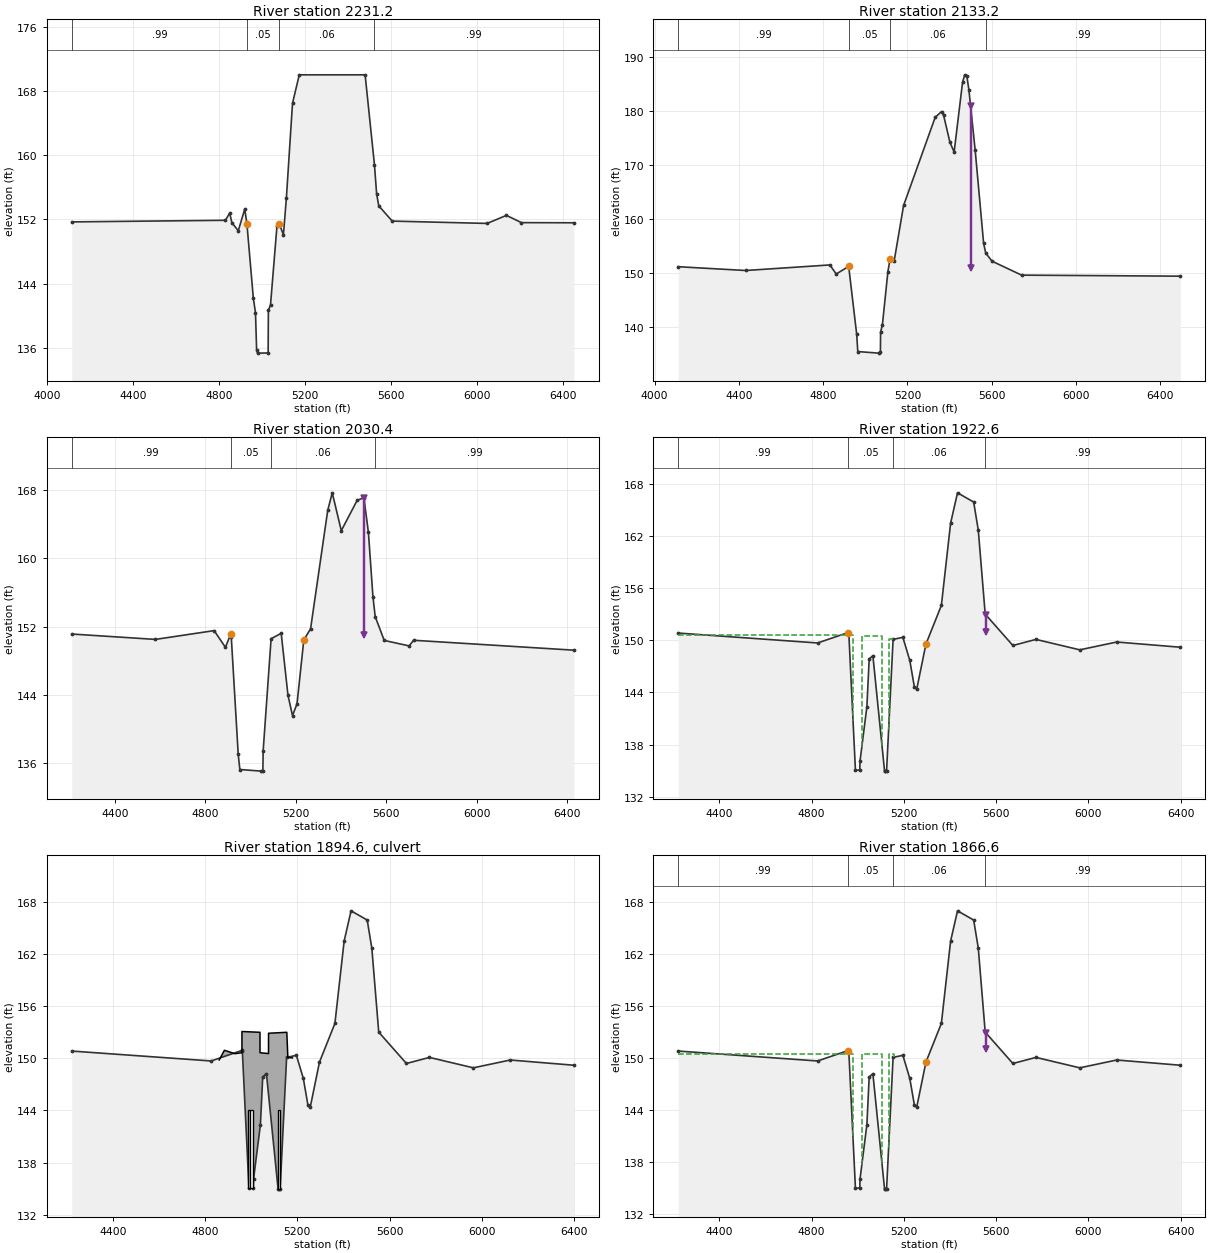
Type RM Length L Ch R = 1 ,2231.2  ,99.9,98,89.6
BEGIN DESCRIPTION:
K159-00-00-S-0-2a_DAM - XS2
Located At: SHEET PILING DROP STRUCTURE 5000 FT D/S HWY 290 AND 330 FT U/S OF CULVERTS
Elevations greater than 170.00 on the ROB were truncated.
Detention basin on ROB from K159-00 mouth to XS 2252.2
END DESCRIPTION:
XS GIS Cut Line= 5
      3005506.85     13914549.79      3004709.77     13914513.27
      3004549.07     13914508.93      3004014.92     13914491.28
      3003176.97     13914616.06
#Sta/Elev= 30
  4115.4   151.7  4830.6   151.9  4850.6   152.8  4860.6   151.6  4890.6   150.6
  4920.6   153.3  4930.5   151.5  4930.6   151.5  4960.6   142.2  4970.6   140.4
  4975.9  135.76  4980.2  135.38  5029.5   135.4  5030.6   140.7  5040.6   141.4
  5070.6   151.2  5080.5   151.5  5100.6   150.1  5114.4  154.66  5142.9  166.45
  5174.4  169.99  5480.9  169.99  5524.4   158.8  5534.4   155.2  5544.4   153.7
  5607.1   151.8  6048.7  151.51  6138.7  152.51  6208.7  151.61  6452.5  151.59
#Mann= 4 ,-1 , 0
  4115.4     .99       0  4930.6     .05       0  5080.5     .06       0
  5524.4     .99       0
Bank Sta=4930.5,5080.5
XS Rating Curve= 0
Exp/Cntr=.7,.5

Type RM Length L Ch R = 1 ,2133.2  ,102,102.8,117.9
BEGIN DESCRIPTION:
K159-00-00-S-0-2a_DAM - XS1
END DESCRIPTION:
XS GIS Cut Line= 6
      3005511.42     13914449.89      3004713.41     13914413.34
      3004576.89      13914410.5      3004486.35     13914495.81
      3004016.26     13914476.66      3003171.83     13914598.53
#Sta/Elev= 30
  4112.2  151.24  4432.2  150.54  4832.2  151.57  4862.2  149.89 4921.36   151.3
 4959.48  138.69 4964.54  135.53 5063.65  135.24 5071.95   135.4 5072.89  139.12
 5081.44  140.51  5107.6  150.34  5117.6  152.61  5137.6  152.37    5182  162.58
    5332   178.9    5362  179.96    5372  179.27    5402  174.28    5422  172.48
    5462   185.4    5472  186.77    5482  186.63    5492     184    5522  172.76
    5562  155.55    5572  153.76    5602  152.26  5742.5  149.68  6495.7  149.49
#Mann= 4 ,-1 , 0
  4112.2     .99       0 4921.36     .05       0  5117.6     .06       0
    5572     .99       0
Levee=0,,,-1,5500,151,,
Bank Sta=4921.36,5117.6
XS Rating Curve= 0
Exp/Cntr=.3,.1

Type RM Length L Ch R = 1 ,2030.4  ,100,107.8,92.6
BEGIN DESCRIPTION:
K159-00-00-S-0-2b_Pr. Culv - XS4
END DESCRIPTION:
XS GIS Cut Line= 5
       3005417.5     13914358.87      3004673.82     13914309.32
      3004512.47     13914306.03      3004315.72     13914394.83
      3003222.32     13914506.26
#Sta/Elev= 30
  4208.9  151.14  4578.9  150.51  4838.9  151.54  4888.9  149.58 4911.56   151.1
 4914.64  150.82 4945.38  137.07 4952.63  135.28 5048.17  135.09  5054.5  135.12
 5055.77  137.46 5090.91  150.59  5135.6  151.22  5165.6  143.96  5185.6  141.59
  5205.6  142.97  5235.6  150.43  5265.6  151.76  5341.5  165.62  5361.5  167.67
  5401.5  163.24  5471.5  166.78  5501.5  167.11  5521.5  163.03  5541.5  155.52
  5551.5  153.18  5591.5  150.39  5701.5  149.75  5721.5  150.41  6430.5  149.25
#Mann= 4 ,-1 , 0
  4208.9     .99       0 4911.56     .05       0 5090.91     .06       0
  5551.5     .99       0
Levee=0,,,-1,5500,151,,
#XS Ineff= 2 , 0
       0 4911.56   150.6               0
Permanent Ineff=
       F       F
Bank Sta=4911.56,5235.6
XS Rating Curve= 0
Exp/Cntr=.5,.3

Type RM Length L Ch R = 1 ,1922.6  ,61.9,56,55.7
BEGIN DESCRIPTION:
K159-00-00-S-0-2b_Pr. Culv - XS3
Detention basin on ROB from K159-00 mouth to XS 2252.2
The levee set on the right overbank at station 5500 is used to isolate the far ROB detention basin and is not intended as a certified flood-control levee.
END DESCRIPTION:
XS GIS Cut Line= 5
        3005424.       13914259.      3004677.96     13914209.38
      3004592.04     13914207.97      3004335.84     13914312.99
      3003275.96     13914425.66
#Sta/Elev= 30
  4222.3  150.83  4826.6  149.69  4958.6  150.89  4961.5  150.94  4990.5  135.02
  5009.5  135.09  5010.2  136.07  5040.1  142.36  5050.1  147.85  5066.1  148.23
  5116.6  134.98  5120.6  134.94  5125.5  134.97  5153.7   150.1  5196.1  150.34
  5226.1  147.68  5246.1  144.61  5256.1  144.37  5296.1  149.56    5363  154.01
    5403  163.48    5433  166.97    5503  165.91    5523  162.68    5553  153.01
    5673   149.4    5773   150.1    5963   148.9    6123   149.8  6398.8   149.2
#Mann= 4 ,-1 , 0
  4222.3     .99       0  4958.6     .05       0  5153.7     .06       0
    5553     .99       0
Levee=0,,,-1,5557.2,151,,
#XS Ineff= 3 ,-1
  4222.3  4980.2   150.6  5018.2  5106.2   150.5  5134.2  5157.2   150.1
Permanent Ineff=
       F       F       F
Bank Sta=4958.6,5296.1
XS Rating Curve= 0
Exp/Cntr=.5,.3

Type RM Length L Ch R = 2 ,1894.6  ,,,
BEGIN DESCRIPTION:
MULTIPLE OPENING 5300 FT D/S HWY 290
Structure ID: K159-00-00-S-0-2b
END DESCRIPTION:
Bridge Culvert--1,0,-1,-1, 0
Deck Dist Width WeirC Skew NumUp NumDn MinLoCord MaxHiCord MaxSubmerge Is_Ogee
10,36,3,0, 12, 12, , , .95, 0, ,,,
  4861.4    4884  4929.2 4959.99    4960  5038.2  5038.3  5075.2  5075.3  5154.5
  5159.1  5179.2
  149.81  150.92  150.53  150.64  153.08  152.99  150.64  150.54  152.88  152.99
  150.09  150.04
                                                                                
                
  4861.4    4884  4929.2 4959.99    4960  5038.2  5038.3  5075.2  5075.3  5154.5
  5159.1  5179.2
  149.81  150.92  150.53  150.64  153.08  152.99  150.64  150.54  152.88  152.99
  150.09  150.04
                                                                                
                
BR Coef= 1 , 1 , 0 ,1.25, 0 ,,,.8,-1,2,0,
WSPro=,,,, 1 ,,,, 0 ,,,, 0 ,,,,-1 ,-1 ,-1 , 0 , 0 , 0 , 0 , 0
Culvert=2,9,6,36,.015,.4,1,8,1,135.03,4991,135.15,4991,Culvert #1  , 0 ,10
Culvert Bottom n=.015
Culvert=2,9,12,36,.015,.4,1,8,1,135.04,5003,135,5003,Culvert #2  , 0 ,10
Culvert Bottom n=.015
Culvert=2,9,9,36,.015,.4,1,8,1,134.99,5121,134.93,5121,Culvert #3  , 0 ,10
Culvert Bottom n=.015
BC Design=,, 0 ,, 0 ,,,,,,
BC HTab HWMax=166.97

Type RM Length L Ch R = 1 ,1866.6  ,99.5,100.6,108.4
BEGIN DESCRIPTION:
K159-00-00-S-0-2b_Pr. Culv - XS2
Detention basin on ROB from K159-00 mouth to XS 2252.2.
The 1% floodplain spills towards the Cypress Creek watershed on the ROB (the detention basin) at a location where the tributary is within the receiving's stream backwater.
The levee set on the right overbank at station 5500 is used to isolate the far ROB detention basin and is not intended as a certified flood-control levee.
END DESCRIPTION:
XS GIS Cut Line= 5
        3005429.       13914201.      3004683.96     13914147.82
      3004593.95     13914146.34      3004322.68     13914258.49
      3003276.09     13914364.33
#Sta/Elev= 30
  4222.3  150.81  4826.6  149.67  4958.6  150.87  4961.5  150.92  4990.5     135
  5009.5  135.07  5010.2  136.05  5040.1  142.34  5050.1  147.83  5066.1  148.21
  5116.6  134.96  5120.6  134.92  5125.5  134.95  5153.7  150.08  5196.1  150.32
  5226.1  147.66  5246.1  144.59  5256.1  144.35  5296.1  149.54    5363  153.99
    5403  163.46    5433  166.95    5503  165.89    5523  162.66    5553  152.99
    5673  149.38    5773  150.08    5963  148.88    6123  149.78  6398.8  149.18
#Mann= 4 ,-1 , 0
  4222.3     .99       0  4958.6     .05       0  5153.7     .06       0
    5553     .99       0
Levee=0,,,-1,5557.2,151,,
#XS Ineff= 3 ,-1
  4222.3  4980.2  150.48  5018.2  5106.2  150.48  5134.2  5157.2  150.48
Permanent Ineff=
       F       F       F
Bank Sta=4958.6,5296.1
XS Rating Curve= 0
Exp/Cntr=.5,.3

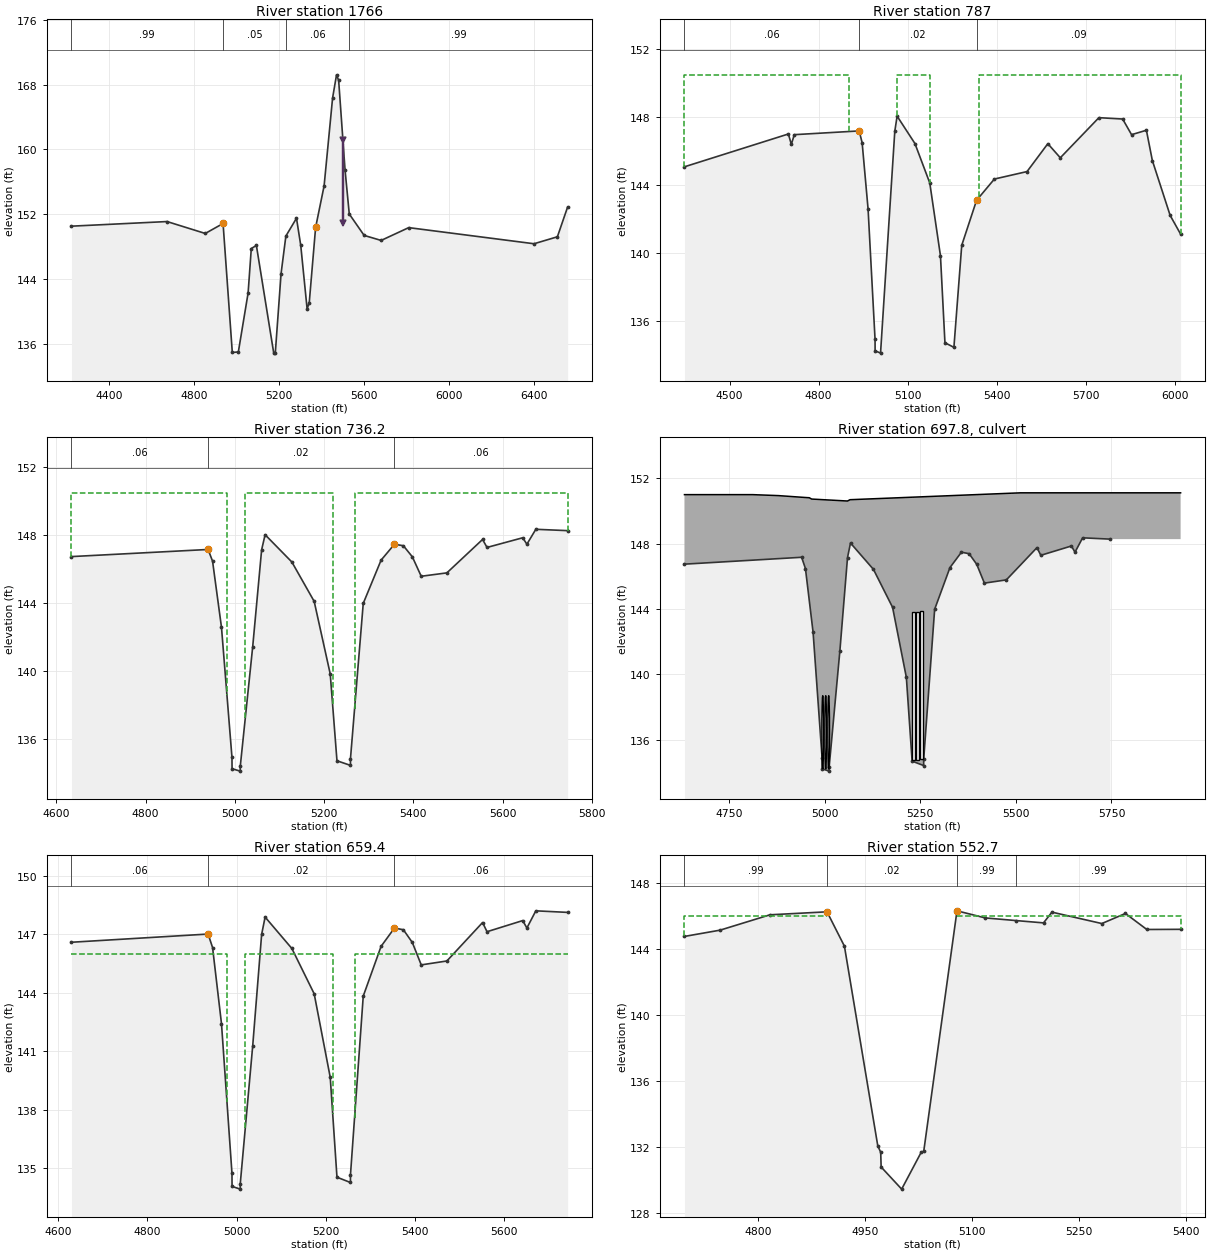
Type RM Length L Ch R = 1 ,1766    ,986.1,979,973.4
BEGIN DESCRIPTION:
K159-00-00-S-0-2b_Pr. Culv - XS1
Detention basin on ROB from K159-00 mouth to XS 2252.2.
The 1% floodplain spills towards the Cypress Creek watershed on the ROB (the detention basin) at a location where the tributary is within the receiving's stream backwater.
The levee set on the right overbank at station 5500 is used to isolate the far ROB detention basin and is not intended as a certified flood-control levee.
END DESCRIPTION:
XS GIS Cut Line= 5
      3005408.57     13914106.61      3004715.47     13914043.89
       3004561.8     13914047.02      3004201.14     13914216.38
      3003119.14     13914332.42
#Sta/Elev= 30
  4221.9  150.52  4671.9  151.09  4851.9  149.624935.725  150.854979.225  134.93
5007.725     1355053.625  142.275068.625  147.765092.625  148.145174.375  134.85
5181.725  134.885208.875  144.67  5231.5   149.3  5281.5   151.5  5301.5  148.15
  5331.5  140.31  5341.5  141.07  5371.5  150.36  5411.5  155.49  5451.5  166.35
    5470   169.2    5480  168.51    5510  157.49    5530  152.02    5600  149.38
    5680  148.76    5810  150.34    6400  148.35    6510  149.21  6558.2  152.89
#Mann= 4 ,-1 , 0
  4221.9     .99       04935.725     .05       0  5231.5     .06       0
    5530     .99       0
Levee=0,,,-1,5500,150.93,,
#XS Ineff= 1 ,-1
  4221.9 4935.73  150.41
Permanent Ineff=
       F
Bank Sta=4935.725,5371.5
XS Rating Curve= 0
Exp/Cntr=.3,.1

Type RM Length L Ch R = 1 ,787     ,55.2,50.8,49.6
BEGIN DESCRIPTION:
K159-00-00-S-0-1a_Pr. Culv - XS4
Detention basin on ROB from K159-00 mouth to XS 2252.2
Detention basin on LOB from K159-00 mouth to about 200' downstream of XS 1866.6
END DESCRIPTION:
XS GIS Cut Line= 5
      3005091.82     13912773.72       3004620.2     13913062.07
       3004420.2      13913083.5      3003993.43     13913347.78
      3003611.53     13913510.73
#Sta/Elev= 30
    4348  145.09    4698  147.02    4708  146.41    4718  146.98 4936.45   147.2
 4946.45  146.51 4966.45  142.61 4989.95  134.94 4990.15  134.27 5008.45  134.13
 5056.45  147.18 5064.25  148.07 5124.25  146.46 5174.25  144.14 5210.25  139.86
 5225.35  134.74 5255.55  134.47  5281.9  140.47  5331.9  143.12  5391.9  144.37
  5501.9  144.81  5571.9  146.45  5613.9  145.62  5743.9  147.98  5823.9   147.9
  5853.9  146.98  5903.9  147.24  5923.9  145.46  5983.9  142.23  6019.1  141.13
#Mann= 3 ,-1 , 0
    4348     .06       0 4936.45     .02       0  5331.9     .09       0
#XS Ineff= 3 ,-1
    4348  4901.6   150.5 5064.25 5174.25   150.5  5341.2  6019.1   150.5
Permanent Ineff=
       F       F       F
Bank Sta=4936.45,5331.9
XS Rating Curve= 0
Exp/Cntr=.5,.3

Type RM Length L Ch R = 1 ,736.2   ,72.9,76.8,62.8
BEGIN DESCRIPTION:
K159-00-00-S-0-1a_Pr. Culv - XS3
Detention basin on ROB from K159-00 mouth to XS 2252.2
Detention basin on LOB from K159-00 mouth to about 200' downstream of XS 1866.6
END DESCRIPTION:
XS GIS Cut Line= 6
      3004852.08     13912900.35       3004700.9     13912995.03
      3004447.19       13913027.       3004146.8     13913238.63
      3003956.13      13913347.3      3003872.38     13913383.54
#Sta/Elev= 30
  4633.7  146.74    4940  147.16    4950  146.47    4970  142.57  4993.5   134.9
  4993.7  134.23    5012  134.09  5012.1  134.37    5040  141.43    5060  147.14
  5067.8  148.03  5127.8  146.42  5177.8   144.1  5213.8  139.82  5228.9   134.7
  5259.1  134.43  5259.2  134.83  5287.8  143.98  5327.8  146.53  5357.8  147.47
  5377.8  147.38  5397.8  146.73  5417.8  145.58  5475.3  145.78  5555.3  147.75
  5565.3  147.28  5645.3  147.85  5654.7  147.47  5674.7  148.35    5746  148.27
#Mann= 3 ,-1 , 0
  4633.7     .06       0    4940     .02       0  5357.8     .06       0
#XS Ineff= 3 ,-1
  4633.7  4982.3   150.5  5023.3  5219.3   150.5  5268.3    5746   150.5
Permanent Ineff=
       F       F       F
Bank Sta=4940,5357.8
XS Rating Curve= 0
Exp/Cntr=.5,.3

Type RM Length L Ch R = 2 ,697.8   ,,,
BEGIN DESCRIPTION:
MULTIPLE OPENING 6375 FT DS HWY 290
Structure ID: K159-00-00-S-0-1a
END DESCRIPTION:
Bridge Culvert--1,0,-1,-1, 0
Deck Dist Width WeirC Skew NumUp NumDn MinLoCord MaxHiCord MaxSubmerge Is_Ogee
10,55,3,0, 31, 31, , , .95, 0, ,,,
  4633.7  4756.9  4766.9  4776.9  4796.9  4806.9    4812  4879.7  4946.6  4960.1
  4966.2  5059.9  5066.5  5511.9  5541.8  5541.9  5561.7  5581.7  5591.7  5611.7
  5621.7  5641.7  5701.7  5721.7  5731.7  5761.7  5781.1  5871.1  5891.1  5921.1
  5930.8
  150.99  150.99  150.99  150.99  150.99  150.99  150.99  150.93  150.82   150.8
  150.72   150.6  150.68   151.1   151.1   151.1   151.1   151.1   151.1   151.1
   151.1   151.1   151.1   151.1   151.1   151.1   151.1   151.1   151.1   151.1
   151.1
                                                                                
                                                                                
                                                                                
        
  4633.7  4756.9  4766.9  4776.9  4796.9  4806.9    4812  4879.7  4946.6  4960.1
  4966.2  5059.9  5066.5  5511.9  5541.8  5541.9  5561.7  5581.7  5591.7  5611.7
  5621.7  5641.7  5701.7  5721.7  5731.7  5761.7  5781.1  5871.1  5891.1  5921.1
  5930.8
  150.99  150.99  150.99  150.99  150.99  150.99  150.99  150.93  150.82   150.8
  150.72   150.6  150.68   151.1   151.1   151.1   151.1   151.1   151.1   151.1
   151.1   151.1   151.1   151.1   151.1   151.1   151.1   151.1   151.1   151.1
   151.1
                                                                                
                                                                                
                                                                                
        
BR Coef= 1 , 1 , 0 ,1.25, 0 ,,,.8,0,2,0,
WSPro=,,,, 1 ,,,, 0 ,,,, 0 ,,,,-1 ,-1 ,-1 , 0 , 0 , 0 , 0 , 0
Culvert=1,4.5,,55,.015,.4,1,1,3,134.21,4995.2,134.57,4995.2,Culvert #1  , 0 ,10
Culvert Bottom n=.015
Culvert=1,4.5,,55,.015,.4,1,1,3,134.21,5003,134.6,5003,Culvert #2  , 0 ,10
Culvert Bottom n=.015
Culvert=1,4.5,,55,.015,.4,1,1,3,134.21,5010.8,134.43,5010.8,Culvert #3  , 0 ,10
Culvert Bottom n=.015
Culvert=2,9,8,55,.015,.4,1,8,1,134.79,5232.8,134.57,5232.8,Culvert #4  , 0 ,10
Culvert Bottom n=.015
Culvert=2,9,8,55,.015,.4,1,8,1,134.8,5244,134.6,5244,Culvert #5  , 0 ,10
Culvert Bottom n=.015
Culvert=2,9,8,55,.015,.4,1,8,1,134.86,5254.3,134.43,5254.3,Culvert #6  , 0 ,10
Culvert Bottom n=.015
BC Design=,, 0 ,, 0 ,,,,,,
BC HTab HWMax=148.43

Type RM Length L Ch R = 1 ,659.4   ,106.4,106.7,119.5
BEGIN DESCRIPTION:
K159-00-00-S-0-1a_Pr. Culv - XS2
Detention basin on ROB from K159-00 mouth to XS 2252.2
Detention basin on LOB from K159-00 mouth to about 200' downstream of XS 1866.6
END DESCRIPTION:
XS GIS Cut Line= 6
        3004841.       13912834.       3004667.9     13912932.12
       3004457.5     13912952.74      3004136.27     13913172.85
      3003946.02     13913281.27      3003849.41     13913323.09
#Sta/Elev= 30
  4629.8  146.58  4936.1     147  4946.1  146.31  4966.1  142.41  4989.6  134.74
  4989.8  134.07  5008.1  133.93  5008.2  134.21  5036.1  141.27  5056.1  146.98
  5063.9  147.87  5123.9  146.26  5173.9  143.94  5209.9  139.66    5225  134.54
  5255.2  134.27  5255.3  134.67  5283.9  143.82  5323.9  146.37  5353.9  147.31
  5373.9  147.22  5393.9  146.57  5413.9  145.42  5471.4  145.62  5551.4  147.59
  5561.4  147.12  5641.4  147.69  5650.8  147.31  5670.8  148.19  5742.1  148.11
#Mann= 3 ,-1 , 0
  4629.8     .06       0  4936.1     .02       0  5353.9     .06       0
#XS Ineff= 3 ,-1
  4629.8  4978.4     146  5019.4  5215.4     146  5264.4  5742.1     146
Permanent Ineff=
       F       F       F
Bank Sta=4936.1,5353.9
XS Rating Curve= 0
Exp/Cntr=.5,.3

Type RM Length L Ch R = 1 ,552.7   ,20.8,21,22.3
BEGIN DESCRIPTION:
K159-00-00-S-0-1b_DAM - XS3
Detention basin on ROB from K159-00 mouth to XS 2252.2
Detention basin on LOB from K159-00 mouth to about 200' downstream of XS 1866.6
END DESCRIPTION:
XS GIS Cut Line= 5
        3004757.       13912709.      3004576.97     13912830.91
      3004469.17      13912840.7      3004198.67     13912877.83
      3004101.69     13912887.77
#Sta/Elev= 20
  4696.3  144.76  4746.3  145.14  4816.3  146.07  4896.3  146.25  4920.7  144.17
  4967.5  132.08  4971.6  131.69  4972.2   130.8    5001  129.46  5028.4  131.69
    5032  131.76  5078.6  146.31  5118.3  145.88  5161.5  145.72    5200  145.58
  5211.8  146.23  5281.8  145.54  5314.9  146.15  5344.9  145.18  5392.3  145.19
#Mann= 4 ,-1 , 0
  4696.3     .99       0  4896.3     .02       0  5078.6     .99       0
  5161.5     .99       0
#XS Ineff= 2 , 0
       0  4896.3     146  5078.6       0     146
Permanent Ineff=
       F       F
Bank Sta=4896.3,5078.6
XS Rating Curve= 0
Exp/Cntr=.7,.5