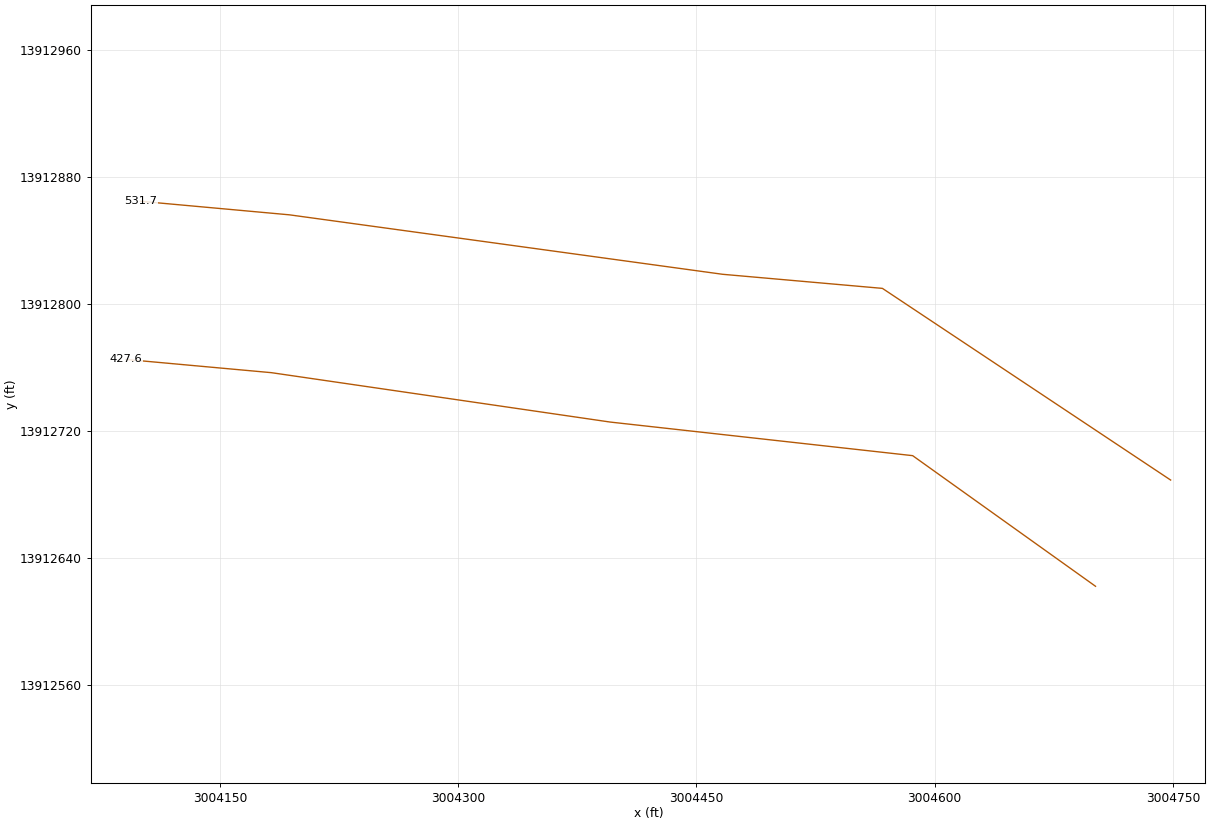
HEC-RAS study K159-00-00.prj: K159-00-00

--- K159-00-00.g01 (geometry) --- (continued)

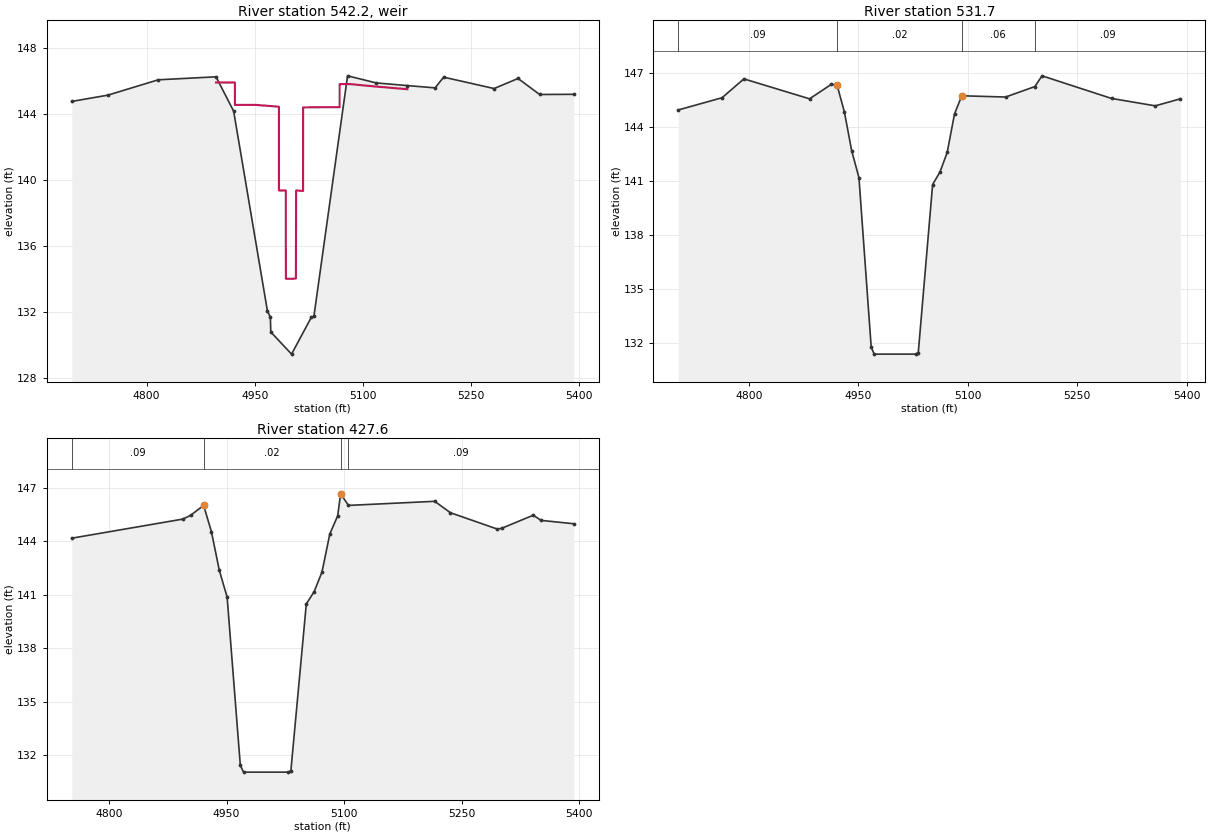
Type RM Length L Ch R = 5 ,542.2   ,,,
BEGIN DESCRIPTION:
SHEET PILING STRUCTURE 6500 FT D/S HWY 290 (S1 PER PHOTOS) AND 125 FT D/S CULVERTS
Structure ID: K159-00-00-S-0-1b
END DESCRIPTION:
IW Pilot Flow=0
#Inline Weir SE= 21
  4896.3  145.91  4922.4  145.91 4922.41  144.55  4951.2  144.55  4983.5  144.44
 4983.51  139.37    4993  139.37  4993.1  134.03  4999.9  134.02    5001  134.02
    5007  134.04  5007.3  139.37  5016.9  139.34    5017   144.4    5049  144.41
  5067.6  144.41 5067.61  145.81  5078.6  145.81  5081.5  145.81  5118.3  145.66
  5161.5   145.5
IW Dist,WD,Coef,Skew,MaxSub,Min_El,Is_Ogee,SpillHt,DesHd
10,1,3,0,.95,, 0 ,,,100,100,

Type RM Length L Ch R = 1 ,531.7   ,102.3,104.1,101.4
BEGIN DESCRIPTION:
K159-00-00-S-0-1b_DAM - XS2
Located At: SHEET PILING STRUCTURE 6500 FT D/S HWY 290 (S1 PER PHOTOS) AND 125 FT D/S CULVERTS
Detention basin on ROB from K159-00 mouth to XS 2252.2
Detention basin on LOB from K159-00 mouth to about 200' downstream of XS 1866.6
END DESCRIPTION:
XS GIS Cut Line= 5
       3004748.6       13912689.      3004567.13     13912809.68
      3004466.53     13912818.55      3004193.76     13912855.99
      3004099.98     13912864.53
#Sta/Elev= 24
    4703  144.95    4763  145.63    4793  146.68    4883  145.57    4913  146.38
  4920.7  146.33  4930.7  144.85  4940.7  142.69  4950.7  141.18  4967.5  131.75
  4971.6  131.36  5028.4  131.36    5032  131.43  5051.7   140.8  5061.7  141.49
  5071.7  142.59  5081.7  144.73  5091.7  145.74  5151.7  145.67  5191.7  146.25
  5201.7  146.85    5297  145.59    5357  145.18  5391.2  145.57
#Mann= 4 ,-1 , 0
    4703     .09       0  4920.7     .02       0  5091.7     .06       0
  5191.7     .09       0
Bank Sta=4920.7,5091.7
XS Rating Curve= 0
Exp/Cntr=.7,.5

Type RM Length L Ch R = 1 ,427.6   ,0,0,0
BEGIN DESCRIPTION:
K159-00-00-S-0-1b_DAM - XS1
Detention basin on ROB from K159-00 mouth to XS 2252.2
Detention basin on LOB from K159-00 mouth to about 200' downstream of XS 1866.6
END DESCRIPTION:
XS GIS Cut Line= 5
       3004701.3     13912622.12      3004586.17     13912704.36
      3004395.85      13912725.5      3004182.42     13912756.61
      3004090.92     13912764.94
#Sta/Elev= 25
  4752.5  144.18    4894  145.25    4904  145.46  4920.7  146.02  4930.7  144.54
  4940.7  142.38  4950.7  140.87  4967.5  131.44  4971.6  131.05  5028.4  131.05
    5032  131.12  5051.7  140.49  5061.7  141.18  5071.7  142.28  5081.7  144.42
  5091.7  145.43  5095.5  146.67  5105.5  146.02  5215.5  146.25  5235.5  145.61
  5295.5  144.69  5301.2  144.74  5341.2  145.47  5351.2  145.18    5393  144.99
#Mann= 4 ,-1 , 0
  4752.5     .09       0  4920.7     .02       0  5095.5     .06       0
  5105.5     .09       0
Bank Sta=4920.7,5095.5
XS Rating Curve= 0
Exp/Cntr=.3,.1

Chan Stop Cuts=-1